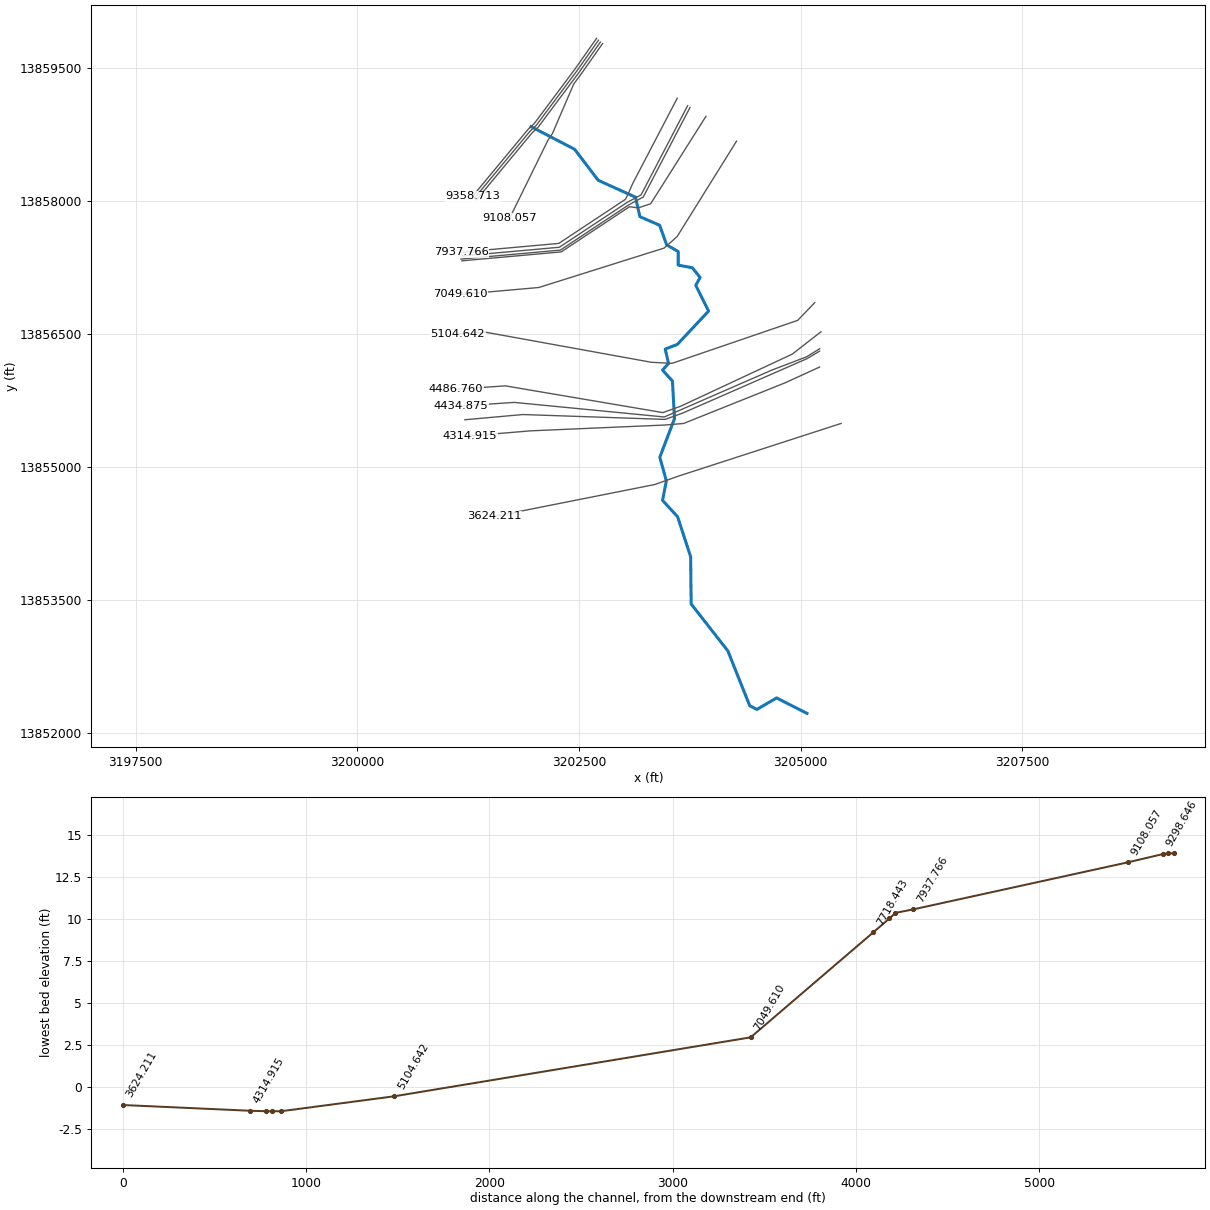
--- G103-01-00.prj (project) ---

Proj Title=G103-01-00
Current Plan=p07
Default Exp/Contr=.3,.1
English Units
Geom File=g10
Flow File=f01
Flow File=f03
Plan File=p07
Plan File=p04
Y Axis Title=Elevation
X Axis Title(PF)=Main Channel Distance
X Axis Title(XS)=Station
BEGIN DESCRIPTION:
HCFCD Unit G103-01-00
(Flood Hazard, Flood Way) Model
10, 2, 1, 0.2% Event
Filename G1030000.prj
Prepared by:  Dannenbaum Engineering Corp.  	Date:  1-14-04
Reviewed by:			                Date:
STATUS (Draft)
END DESCRIPTION:
DSS File=dss
DSS Export Rating Curves= 0
DSS Export Rating Curve Sorted= 0
DSS Export Volume Flow Curves= 0
DXF OffsetX= 0
DXF OffsetY= 0
DXF ScaleX= 1
DXF ScaleY= 10

--- G103-01-00.p07 (plan) ---

Plan Title=FEMA Effective June 2007
Version=Version 3.0.1  Mar 2001
Short Identifier=FEMAeff0607
Geom File=g10
Flow File=f01
Subcritical Flow
K Sum by GR= 0
Std Step Tol= 0.01
Critical Tol= 0.01
Num of Std Step Trials= 20
Max Error Tol= 0.3
Flow Tol Ratio= 0.001
Split Flow NTrial= 30
Split Flow Tol= 0.02
Split Flow Ratio= 0.02
Log Output Level= 0
Friction Slope Method= 1
Unsteady Friction Slope Method= 2
Parabolic Critical Depth
Global Vel Dist= 0 , 0 , 0
Global Log Level= 0
CheckData=True
Encroach Param=-1 ,0,0, 0
BEGIN DESCRIPTION:
This plan runs the flood hazard flows (10%, 2%, 1% and 0.2%) through G103-01-00.  Flows were extracted from the HEC-HMS model for G103-01-00.
END DESCRIPTION:
Computation Interval=1HOUR
Output Interval=1HOUR
Run HTab= 0
Run UNet= 0
Run PostProcess= 0
UNET Theta= 1
UNET ZTol= 0.02
UNET ZSATol= 0.1
UNET MxIter= 20
UNET MaxInSteps= 20
UNET DtIC= 0
UNET DtMin= 0
UNET MaxCRTS= 20
UNET WFStab= 2
UNET SFStab= 1
UNET WFX= 1
UNET SFX= 1
UNET Convert EG Bridges=-1
UNET Use Existing IB Tables=-1
Instantaneous Interval=1HOUR
Write IC File= 0
Write Velocity= 0
Write Detailed= 0

--- G103-01-00.p04 (plan) ---

Plan Title=Floodway
Version=Version 3.0.1  Mar 2001
Short Identifier=Floodway0607
Geom File=g10
Flow File=f03
Subcritical Flow
K Sum by GR= 0
Std Step Tol= 0.01
Critical Tol= 0.01
Num of Std Step Trials= 20
Max Error Tol= 0.3
Flow Tol Ratio= 0.001
Split Flow NTrial= 30
Split Flow Tol= 0.02
Split Flow Ratio= 0.02
Log Output Level= 0
Friction Slope Method= 1
Unsteady Friction Slope Method= 2
Parabolic Critical Depth
Global Vel Dist= 0 , 0 , 0
Global Log Level= 0
CheckData=True
Encroach Param= 0 ,0,0, 5
Encroach River=G103-01-00
Encroach Reach=Main
Encroach Node=9358.713
       1 1202.76 1282.04       1 1202.76 1282.04       4       1
       4     1.1
Encroach Node=9328.676
       1 1216.99 1259.41       1 1216.99 1259.41       4       1
       4     1.1
Encroach Node=9320.776
       1 1216.99 1259.61       1 1216.99 1259.61       4       1
       4     1.1
Encroach Node=9298.646
       1 1216.99 1259.61       1 1216.99 1259.61       4       1
       4     1.1
Encroach Node=9108.057
       1 1183.44 1246.89       1 1183.44 1246.89       4       1
       4     1.1
Encroach Node=7937.766
       1 1149.14 1279.35       1 1149.14 1279.35       4       1
       4     1.1
Encroach Node=7839.563
       1 1135.47  1263.5       1 1135.47  1263.5       4       1
       4     1.1
Encroach Node=7823.41
       1 1129.65 1269.37       1 1129.65 1269.37       4       1
       4     1.1
Encroach Node=7806.521
       1 1129.65 1269.37       1 1129.65 1269.37       4       1
       4     1.1
Encroach Node=7718.443
       1 1247.33 1353.96       1 1247.33 1353.96       4       1
       4     1.1
Encroach Node=7049.610
       1 1320.33 1448.67       1 1320.33 1448.67       4       1
       4     1.1
Encroach Node=5104.642
       1 1758.13 1927.33       1 1758.13 1927.33       4       1
       4     1.1
Encroach Node=4486.760
       1 1807.72 2029.85       1 1807.72 2029.85       4       1
       4     1.1
Encroach Node=4434.875
       1 1758.11 1880.52       1 1758.11 1880.52       4       1
       4     1.1
Encroach Node=4425.625
       1 1758.11 1880.52       1 1758.11 1880.52       4       1
       4     1.1
Encroach Node=4406.046
       1 1758.13 1880.52       1 1758.13 1880.52       4       1
       4     1.1
Encroach Node=4314.915
       1 1715.89 1908.33       1 1715.89 1908.33       4       1
       4     1.1
Encroach Node=3624.211
       1 1957.09 2227.08       1 1957.09 2227.08       4       1
       4     1.1
Encroach Node=2609.976
       1 2081.62 2360.03       1 2081.62 2360.03       4       1
       4     1.1
Encroach Node=2556.055
       1 1863.29 1998.74       1 1863.29 1998.74       4       1
       4     1.1
Encroach Node=2538.555
       1 1863.29 1998.74       1 1863.29 1998.74       4       1
       4     1.1
Encroach Node=2512.657
       1 1863.33 1998.74       1 1863.33 1998.74       4       1
       4     1.1
Encroach Node=2458.607
       1 1811.13 1936.27       1 1811.13 1936.27       4       1
       4     1.1
Encroach Node=2369.607
       1 1811.13 1936.27       1 1811.13 1936.27       4       1
       4     1.1
Encroach Node=2309.604
       1 1813.29  1934.2       1 1813.29  1934.2       4       1
       4     1.1
Encroach Node=2274.468
       1  2256.9  2393.8       1  2256.9  2393.8       4       1
       4     1.1
Encroach Node=2254.867
       1 2256.16 2394.71       1 2256.16 2394.71       4       1
       4     1.1
Encroach Node=2227.982
       1 2256.16 2394.71       1 2256.16 2394.71       4       1
       4     1.1
Encroach Node=2092.500
       1 2272.45 2471.42       1 2272.45 2471.42       4       1
       4     1.1
Encroach Node=1164.962
       1  568.22  648.53       1  568.22  648.53       4       1
       4     1.1
Encroach Node=1118.375
       1  586.88  649.38       1  586.88  649.38       4       1
       4     1.1
Encroach Node=1097.6
       1  586.88  649.38       1  586.88  649.38       4       1
       4     1.1
Encroach Node=1067.170
       1  587.06  649.18       1  587.06  649.18       4       1
       4     1.1
Encroach Node=997.361
       1  585.84  652.83       1  585.84  652.83       4       1
       4     1.1
Encroach Node=952.559
       1  609.43  669.87       1  609.43  669.87       4       1
       4     1.1
Encroach Node=904.203
       1  581.69  693.56       1  581.69  693.56       4       1
       4     1.1
Encroach Node=902
       1   574.7   700.7       1   574.7   700.7       4       1
       4     1.1
Encroach Node=885.695
       1  567.88  683.54       1  567.88  683.54       4       1
       4     1.1
Encroach Node=784.305
       1  578.34  675.28       1  578.34  675.28       4       1
       4     1.1
Encroach Node=386.765
       1   282.7  397.94       1   282.7  397.94       4       1
       4     1.1
Encroach Reach=G103-01-00_0004
Encroach Node=9358.713
       1 1202.76 1282.04       0       0       0       0       0       0
       0       0       0
Encroach Node=9328.676
       1 1216.99 1259.41       0       0       0       0       0       0
       0       0       0
Encroach Node=9320.776
       1 1216.99 1259.61       0       0       0       0       0       0
       0       0       0
Encroach Node=9298.646
       1 1216.99 1259.61       0       0       0       0       0       0
       0       0       0
Encroach Node=9108.057
       1 1183.44 1246.89       0       0       0       0       0       0
       0       0       0
Encroach Node=7937.766
       1 1149.14 1279.35       0       0       0       0       0       0
       0       0       0
Encroach Node=7839.563
       1 1135.47  1263.5       0       0       0       0       0       0
       0       0       0
Encroach Node=7823.41
       1 1129.65 1269.37       0       0       0       0       0       0
       0       0       0
Encroach Node=7806.521
       1 1129.65 1269.37       0       0       0       0       0       0
       0       0       0
Encroach Node=7718.443
       1 1247.33 1353.96       0       0       0       0       0       0
       0       0       0
Encroach Node=7049.610
       1 1320.33 1448.67       0       0       0       0       0       0
       0       0       0
Encroach Node=5104.642
       1 1758.13 1927.33       0       0       0       0       0       0
       0       0       0
Encroach Node=4486.760
       1 1807.72 2029.85       0       0       0       0       0       0
       0       0       0
Encroach Node=4434.875
       1 1758.11 1880.52       0       0       0       0       0       0
       0       0       0
Encroach Node=4425.625
       1 1758.11 1880.52       0       0       0       0       0       0
       0       0       0
Encroach Node=4406.046
       1 1758.13 1880.52       0       0       0       0       0       0
       0       0       0
Encroach Node=4314.915
       1 1715.89 1908.33       0       0       0       0       0       0
       0       0       0
Encroach Node=3624.211
       1 1957.09 2227.08       0       0       0       0       0       0
       0       0       0
Encroach Node=2609.976
       1 2081.62 2360.03       0       0       0       0       0       0
       0       0       0
Encroach Node=2556.055
       1 1863.29 1998.74       0       0       0       0       0       0
       0       0       0
Encroach Node=2538.555
       1 1863.29 1998.74       0       0       0       0       0       0
       0       0       0
Encroach Node=2512.657
       1 1863.33 1998.74       0       0       0       0       0       0
       0       0       0
Encroach Node=2458.607
       1 1811.13 1936.27       0       0       0       0       0       0
       0       0       0
Encroach Node=2369.607
       1 1811.13 1936.27       0       0       0       0       0       0
       0       0       0
Encroach Node=2309.604
       1 1813.29  1934.2       0       0       0       0       0       0
       0       0       0
Encroach Node=2274.468
       1  2256.9  2393.8       0       0       0       0       0       0
       0       0       0
Encroach Node=2254.867
       1 2256.16 2394.71       0       0       0       0       0       0
       0       0       0
Encroach Node=2227.982
       1 2256.16 2394.71       0       0       0       0       0       0
       0       0       0
Encroach Node=2092.500
       1 2272.45 2471.42       0       0       0       0       0       0
       0       0       0
Encroach Node=1164.962
       1  568.22  648.53       0       0       0       0       0       0
       0       0       0
Encroach Node=1118.375
       1  586.88  649.38       0       0       0       0       0       0
       0       0       0
Encroach Node=1097.6
       1  586.88  649.38       0       0       0       0       0       0
       0       0       0
Encroach Node=1067.170
       1  587.06  649.18       0       0       0       0       0       0
       0       0       0
Encroach Node=997.361
       1  585.84  652.83       0       0       0       0       0       0
       0       0       0
Encroach Node=952.559
       1  609.43  669.87       0       0       0       0       0       0
       0       0       0
Encroach Node=904.203
       1  581.69  693.56       0       0       0       0       0       0
       0       0       0
Encroach Node=902
       1   574.7   700.7       0       0       0       0       0       0
       0       0       0
Encroach Node=885.695
       1  567.88  683.54       0       0       0       0       0       0
       0       0       0
Encroach Node=784.305
       1  578.34  675.28       0       0       0       0       0       0
       0       0       0
Encroach Node=386.765
       1   282.7  397.94       0       0       0       0       0       0
       0       0       0
BEGIN DESCRIPTION:
This is the floodway plan (Method 1 and 100-year) for G103-01-00.
END DESCRIPTION:
Computation Interval=1HOUR
Output Interval=1HOUR
Run HTab= 0
Run UNet= 0
Run PostProcess= 0
UNET Theta= 1
UNET ZTol= 0.02
UNET ZSATol= 0.1
UNET MxIter= 20
UNET MaxInSteps= 20
UNET DtIC= 0
UNET DtMin= 0
UNET MaxCRTS= 20
UNET WFStab= 2
UNET SFStab= 1
UNET WFX= 1
UNET SFX= 1
UNET Convert EG Bridges=-1
UNET Use Existing IB Tables=-1
Instantaneous Interval=1HOUR
DSS File=dss
Write IC File= 0
Write Velocity= 0
Write Detailed= 0

--- G103-01-00.f01 (steady flow) ---

Flow Title=FEMA Effective June 2007
Version=Version 3.0.1  Mar 2001
Number of Profiles= 4
Profile Names=10PCT_10yr, 2PCT_50yr, 1PCT_100yr, 0.2PCT_500yr
River Rch & RM=G103-01-00,G103-01-00_0004            ,9358.713
     821    1165    1347    1854
River Rch & RM=G103-01-00,G103-01-00_0004            ,9108.057
     898    1275    1474    2028
River Rch & RM=G103-01-00,G103-01-00_0004            ,7937.766
     913    1297    1499    2063
River Rch & RM=G103-01-00,G103-01-00_0004            ,7718.443
     961    1365    1578    2171
River Rch & RM=G103-01-00,G103-01-00_0004            ,7049.610
    1116    1586    1832    2522
River Rch & RM=G103-01-00,G103-01-00_0004            ,5104.642
    1171    1663    1922    2644
River Rch & RM=G103-01-00,G103-01-00_0004            ,4486.760
    1186    1685    1947    2680
River Rch & RM=G103-01-00,G103-01-00_0004            ,4314.915
    1251    1777    2053    2826
River Rch & RM=G103-01-00,G103-01-00_0004            ,3624.211
    1889    2684    3101    4268
River Rch & RM=G103-01-00,G103-01-00_0004            ,2609.976
    1933    2746    3173    4367
River Rch & RM=G103-01-00,G103-01-00_0004            ,2274.468
    1957    2780    3213    4422
River Rch & RM=G103-01-00,G103-01-00_0004            ,2092.500
    2086    2963    3424    4712
River Rch & RM=G103-01-00,G103-01-00_0004            ,1164.962
    2123    3016    3485    4796
River Rch & RM=G103-01-00,G103-01-00_0004            ,904.203
    2200    3125    3611    4969
Boundary for River Rch & Prof#=G103-01-00,G103-01-00_0004            , 1
Up Type= 0
Dn Type= 3
Dn Slope=.0015
Boundary for River Rch & Prof#=G103-01-00,G103-01-00_0004            , 2
Up Type= 0
Dn Type= 3
Dn Slope=.0015
Boundary for River Rch & Prof#=G103-01-00,G103-01-00_0004            , 3
Up Type= 0
Dn Type= 3
Dn Slope=.0015
Boundary for River Rch & Prof#=G103-01-00,G103-01-00_0004            , 4
Up Type= 0
Dn Type= 3
Dn Slope=.0015
DSS Import GetInterval= 0
DSS Import GetPeak= 0
DSS Import FillOption= 0

--- G103-01-00.f03 (steady flow) ---

Flow Title=Floodway
Version=Version 3.0.1  Mar 2001
Number of Profiles= 2
Profile Names=1PCT_100yr, 1PCTFloodway_100yrFW
River Rch & RM=G103-01-00,G103-01-00_0004            ,9358.713
    1347    1347
River Rch & RM=G103-01-00,G103-01-00_0004            ,9108.057
    1474    1474
River Rch & RM=G103-01-00,G103-01-00_0004            ,7937.766
    1499    1499
River Rch & RM=G103-01-00,G103-01-00_0004            ,7718.443
    1578    1578
River Rch & RM=G103-01-00,G103-01-00_0004            ,7049.610
    1832    1832
River Rch & RM=G103-01-00,G103-01-00_0004            ,5104.642
    1922    1922
River Rch & RM=G103-01-00,G103-01-00_0004            ,4486.760
    1947    1947
River Rch & RM=G103-01-00,G103-01-00_0004            ,4314.915
    2053    2053
River Rch & RM=G103-01-00,G103-01-00_0004            ,3624.211
    3101    3101
River Rch & RM=G103-01-00,G103-01-00_0004            ,2609.976
    3173    3173
River Rch & RM=G103-01-00,G103-01-00_0004            ,2274.468
    3213    3213
River Rch & RM=G103-01-00,G103-01-00_0004            ,2092.500
    3424    3424
River Rch & RM=G103-01-00,G103-01-00_0004            ,1164.962
    3485    3485
River Rch & RM=G103-01-00,G103-01-00_0004            ,904.203
    3611    3611
Boundary for River Rch & Prof#=G103-01-00,G103-01-00_0004            , 1
Up Type= 0
Dn Type= 3
Dn Slope=.0015
Boundary for River Rch & Prof#=G103-01-00,G103-01-00_0004            , 2
Up Type= 0
Dn Type= 3
Dn Slope=.0015
DSS Import GetInterval= 0
DSS Import GetPeak= 0
DSS Import FillOption= 0

--- G103-01-00.g10 (geometry) ---

Geom Title=G103-01-00 June 2007
Version=Version 3.0.1  Mar 2001

River Reach=G103-01-00      ,G103-01-00_0004
Reach XY= 30
     3201958.416    13858840.202     3202450.765     13858584.83
     3202716.832    13858235.001     3203136.839    13858044.703
     3203187.097    13857824.906     3203409.792    13857727.746
     3203488.895    13857506.771     3203619.589    13857431.106
     3203619.589    13857278.057     3203778.657    13857248.823
     3203866.359    13857138.765     3203817.349    13857049.344
     3203961.799    13856759.583     3203609.271    13856383.839
     3203472.559     13856331.39     3203510.391    13856169.743
     3203442.465    13856094.078     3203554.242    13855971.123
       3203577.5       13855547.     3203411.563    13855111.174
     3203485.471    13854845.107     3203442.769    13854625.027
     3203612.438    13854440.081     3203759.498    13853988.397
     3203765.302    13853456.502     3204179.671    13852926.654
        3204426.       13852309.      3204506.25       13852267.
     3204729.474     13852396.75     3205071.532    13852222.523

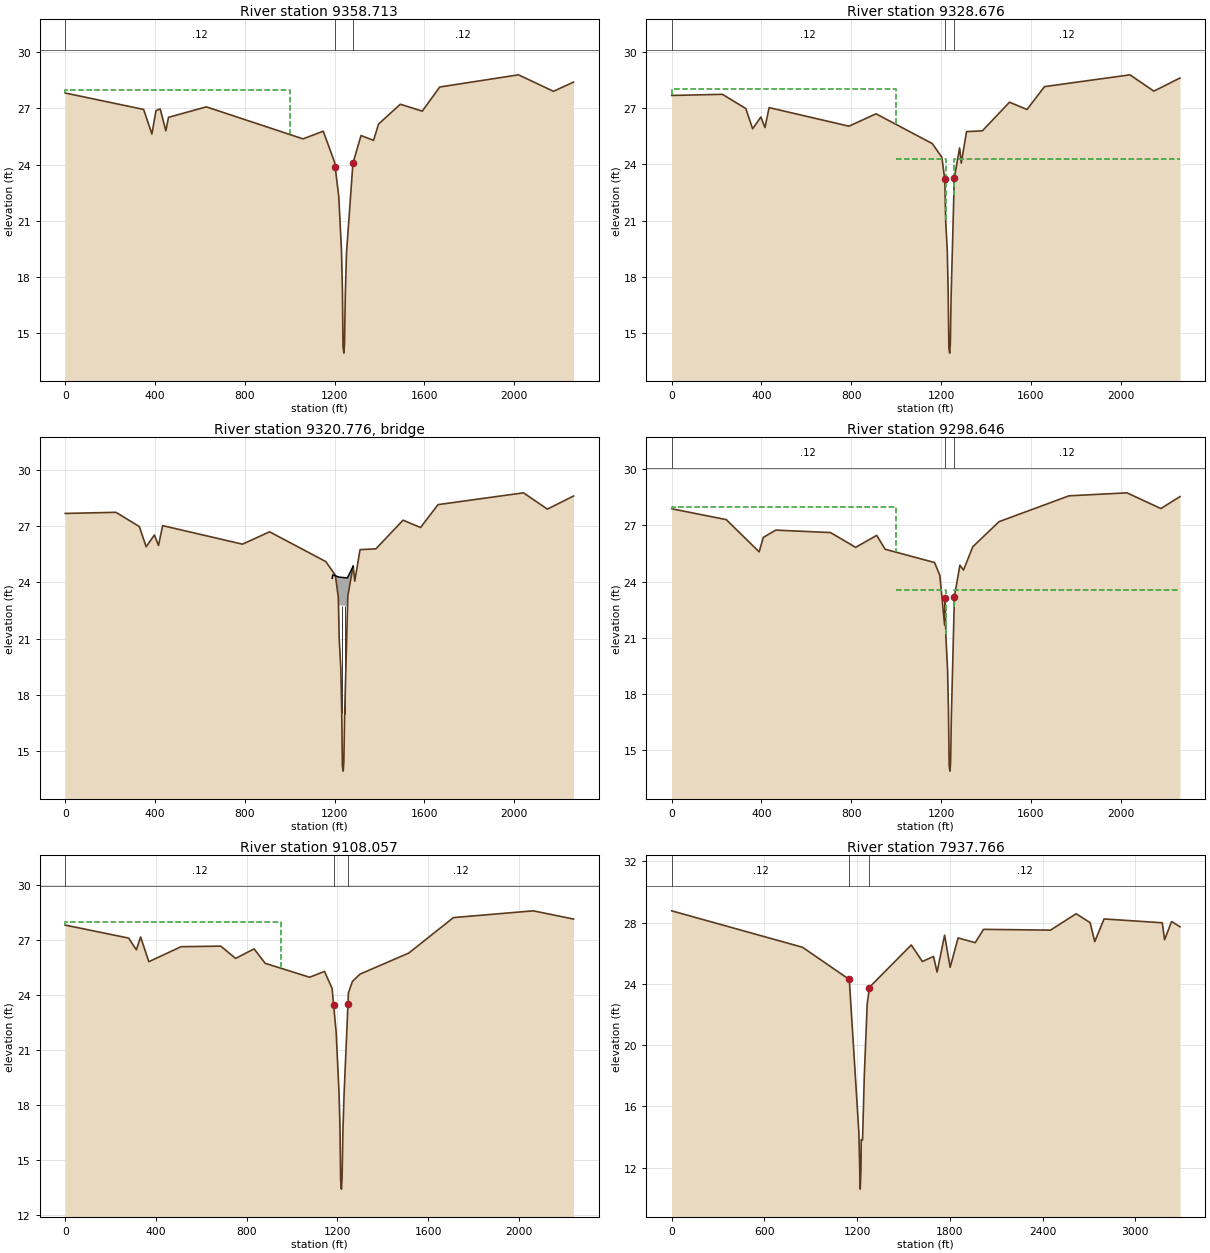
Type RM Length L Ch R = 1 ,9358.713,30.04,30.04,30.03
BEGIN DESCRIPTION:
9358.713
END DESCRIPTION:
XS GIS Cut Line= 6
     3202698.489    13859835.948     3202453.125    13859487.081
     3201994.586    13858873.758     3201937.176    13858820.498
     3201928.242    13858812.209     3201301.073     13858056.19
#Sta/Elev= 30
       0   27.82  349.59   26.94  386.27   25.63   404.6   26.88  423.25   26.97
  448.43    25.8  460.32   26.52  628.88   27.08 1059.64   25.37 1149.85   25.78
  1200.5   24.12 1202.76   23.88 1219.01   22.29 1230.97   19.45 1235.27   17.29
 1238.06   14.28 1241.63   13.93 1244.59   14.45 1247.87   16.89  1253.3   19.26
 1282.04   24.06 1318.14   25.55 1374.01   25.29  1396.1   26.16 1493.55   27.22
    1591   26.85 1668.96   28.14 2019.77   28.79 2175.68   27.91 2265.09    28.4
#Mann= 3 ,-1 , 0
       0     .12       0  1200.5     .06       0 1282.04     .12       0
#XS Ineff= 2 , 0
       0    1000      28               0
Permanent Ineff=
       F       F
Bank Sta=1202.76,1282.04
XS Rating Curve= 0
Exp/Cntr=.5,.3

Type RM Length L Ch R = 1 ,9328.676,30.03,30.03,30.03
BEGIN DESCRIPTION:
9328.676
END DESCRIPTION:
XS GIS Cut Line= 6
     3202720.071    13859815.056     3202474.708    13859466.189
     3202017.951     13858854.52     3201958.759    13858799.606
     3201949.824    13858791.318     3201322.655    13858035.299
#Sta/Elev= 30
       0   27.68   226.1   27.74   330.4   26.98  360.72    25.9   397.4   26.53
  415.74   25.97  434.23   27.03  789.93   26.04  910.71    26.7 1161.41   25.11
  1203.9   24.38 1216.99    23.2 1220.99   20.99 1228.17   19.41 1232.17   17.14
 1235.18    14.2 1238.74   13.93 1241.67   14.42 1244.99   16.86 1259.41   23.28
 1283.07   24.88 1290.39   24.07 1313.88   25.75 1384.36   25.79 1505.42   27.32
 1583.38   26.93 1661.34   28.15 2042.18   28.78 2148.58   27.91 2265.13   28.61
#Mann= 3 ,-1 , 0
       0     .12       0 1216.99     .06       0 1259.41     .12       0
#XS Ineff= 3 ,-1
       0    1000      28    1000  1220.9   24.28  1257.4 2265.13   24.28
Permanent Ineff=
       F       F       F
Bank Sta=1216.99,1259.41
XS Rating Curve= 0
Exp/Cntr=.5,.3

Type RM Length L Ch R = 3 ,9320.776,,,
BEGIN DESCRIPTION:
Footbridge
END DESCRIPTION:
Bridge Culvert--1,0,-1,-1, 0
Deck Dist Width WeirC Skew NumUp NumDn MinLoCord MaxHiCord MaxSubmerge Is_Ogee
1,13.8,2.6,0, 7, 7, , , .95, 0, 0,0,,
  1189.9 1192.33 1220.89  1220.9  1257.4 1257.41  1283.1
   24.22    24.4   24.28   24.28   24.24   24.24   24.86
       0       0       0   22.78   22.74       0       0
  1190.9 1193.33 1221.89  1221.9  1258.4 1258.41  1284.1
   24.22    24.4   24.28   24.28   24.24   24.24   24.86
       0       0       0   22.78   22.74       0       0
Pier Skew, UpSta & Num, DnSta & Num=  ,1232.3, 2 ,1233.3, 2 , 0 , 0 , 0 ,,
       1       1
       0      24
       1       1
       0      24
Pier Skew, UpSta & Num, DnSta & Num=  ,1245.2, 2 ,1245.2, 2 , 0 , 0 , 0 ,,
       1       1
       0      24
       1       1
       0      24
BR Coef=-1 , 1 , 1 ,1.05, 0 ,,,.8,-1,1.2,0,
WSPro=,,,, 1 ,,,, 0 ,,,, 0 ,,,,-1 ,-1 ,-1 , 0 , 0 , 0 , 0 , 0
BC Design=,, 0 ,, 0 ,,,,,,

Type RM Length L Ch R = 1 ,9298.646,185.82,190.59,195.36
BEGIN DESCRIPTION:
9298.646
END DESCRIPTION:
XS GIS Cut Line= 6
     3202741.329    13859793.848     3202495.966    13859444.981
     3202037.426    13858831.657     3201975.467    13858774.067
     3201971.082    13858770.109     3201344.196    13858014.432
#Sta/Elev= 30
       0   27.89   243.1   27.31  389.81   25.59  408.15   26.36  463.94   26.75
  707.42   26.62  819.79   25.83  913.43   26.47  950.89   25.73  1171.3   25.02
 1194.73   24.34 1216.06   21.67 1217.92   23.13    1218    23.2    1222   20.99
 1229.16   19.31 1233.23   17.07  1236.2   14.18 1239.71   13.89 1242.68   14.36
 1245.99   16.79 1259.61    23.2 1284.15   24.88 1300.15   24.62  1341.4   25.86
 1458.34    27.2 1770.02   28.58 2028.45   28.74 2179.45    27.9 2264.64   28.54
#Mann= 3 ,-1 , 0
       0     .12       0    1218     .06       0 1259.61     .12       0
#XS Ineff= 3 ,-1
       0    1000      28    1000  1221.9   23.53  1258.4 2264.64   23.53
Permanent Ineff=
       F       F       F
Bank Sta=1217.92,1259.61
XS Rating Curve= 0
Exp/Cntr=.5,.3

Type RM Length L Ch R = 1 ,9108.057,1168.66,1170.29,1170.84
BEGIN DESCRIPTION:
9108.057
END DESCRIPTION:
XS GIS Cut Line= 6
     3202765.868    13859776.589     3202520.259    13859427.373
     3202440.287    13859320.278     3202201.323    13858763.872
     3202149.843    13858686.505     3201716.611    13857804.907
#Sta/Elev= 30
       0   27.83  279.63   27.12   313.7   26.48  332.63   27.18  368.71   25.83
  510.94   26.65  686.06   26.68  751.34   26.01  832.98   26.53  881.96   25.74
 1077.85   24.98 1143.15    25.3  1176.8   24.37 1183.44   23.47 1194.82   21.96
 1207.33   18.68 1211.65   16.74 1214.39   13.89 1217.92    13.4 1220.84   14.01
 1224.35    16.5 1229.67   18.61 1246.89   23.54 1248.87   24.13 1266.32   24.75
 1299.75   25.15 1514.66    26.3 1711.84   28.24 2063.64   28.61 2241.37   28.16
#Mann= 3 ,-1 , 0
       0     .12       0 1183.44     .06       0 1246.89     .12       0
#XS Ineff= 2 , 0
       0  949.59      28               0
Permanent Ineff=
       F       F
Bank Sta=1183.44,1246.89
XS Rating Curve= 0
Exp/Cntr=.3,.1

Type RM Length L Ch R = 1 ,7937.766,112.49,98.2,83.63
BEGIN DESCRIPTION:
7937.766
END DESCRIPTION:
XS GIS Cut Line= 6
     3203608.247    13859160.539     3203105.058    13858196.455
     3203052.025    13858075.474     3203024.235      13858020.4
     3202271.871    13857522.874     3201170.748    13857423.995
#Sta/Elev= 30
       0   28.77  846.62   26.39 1149.14   24.29 1211.28   14.28 1219.59    10.6
 1224.58   11.78 1226.39   13.83 1234.86    13.8 1246.29      18 1264.93   22.66
 1279.35   23.76 1279.58   23.78 1550.11   26.54 1622.04   25.46 1693.98   25.79
 1717.11   24.77 1765.91   27.18 1801.87   25.08 1853.09      27 1963.72   26.69
 2017.67   27.56 2451.22   27.51 2616.88   28.58 2707.24      28 2737.36   26.76
  2797.6   28.24 3174.11   27.99 3189.17   26.88 3234.35   28.07 3288.82   27.73
#Mann= 3 ,-1 , 0
       0     .12       0 1149.14     .06       0 1279.58     .12       0
Bank Sta=1149.14,1279.35
XS Rating Curve= 0
Exp/Cntr=.5,.3

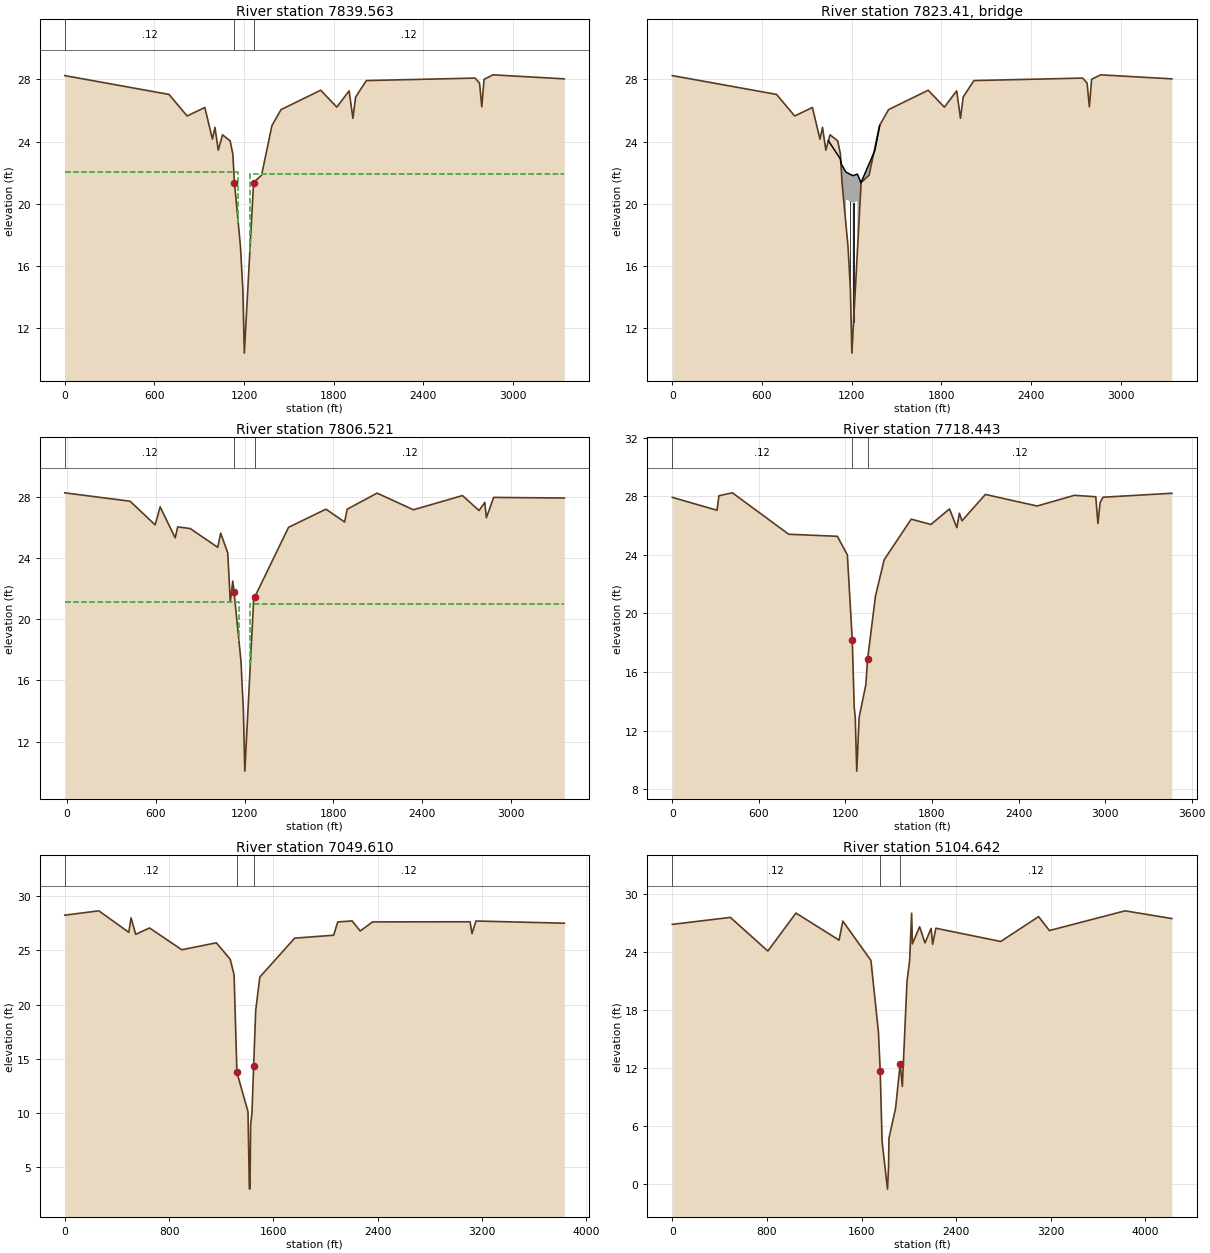
Type RM Length L Ch R = 1 ,7839.563,33.04,33.04,34.42
BEGIN DESCRIPTION:
7839.563
END DESCRIPTION:
XS GIS Cut Line= 6
     3203725.335    13859075.918     3203200.617    13858070.582
     3203199.351    13858069.898     3203043.732     13857985.73
     3202278.341    13857479.588     3201170.219    13857380.081
#Sta/Elev= 30
       0   28.25  697.44   27.04  818.85   25.65  937.29    26.2  988.05   24.16
 1004.97   24.92  1027.3   23.45 1055.73   24.44 1106.49   24.05 1124.56   23.21
 1135.47   21.37 1175.74   17.25 1191.65   14.49 1201.54   10.39  1263.5   21.37
 1316.87   21.84 1386.24   25.03  1446.9   26.06 1712.36   27.31  1820.4   26.22
 1902.92   27.27 1928.29    25.5 1946.28   26.87 2018.21   27.93 2745.41   28.09
 2775.53   27.77 2790.59   26.24 2805.65   28.01 2865.89    28.3 3342.58   28.04
#Mann= 3 ,-1 , 0
       0     .12       0 1135.47     .06       0  1263.5     .12       0
#XS Ineff= 2 , 0
       0 1161.89   22.04  1238.4       0   21.91
Permanent Ineff=
       F       F
Bank Sta=1135.47,1263.5
XS Rating Curve= 0
Exp/Cntr=.5,.3

Type RM Length L Ch R = 3 ,7823.41 ,,,
BEGIN DESCRIPTION:
Oak Lane
END DESCRIPTION:
Bridge Culvert--1,0,-1,-1, 0
Deck Dist Width WeirC Skew NumUp NumDn MinLoCord MaxHiCord MaxSubmerge Is_Ogee
1,30.3,2.6,0, 12, 12, , , .95, 0, 0,0,,
  1043.5  1123.8 1131.39 1161.88 1161.89  1207.4  1238.4 1238.41    1256 1261.61
 1355.31 1387.78
   24.07    22.9   22.54   22.04   22.04   21.81   21.91   21.91   21.51   21.34
   23.43   25.03
       0       0       0       0   20.29   20.06   20.16       0       0       0
       0       0
 1044.06 1124.36 1131.95 1162.44 1162.45 1207.96 1238.96 1238.97 1256.56 1262.17
 1355.87 1388.31
   24.45    22.9   22.54   22.04   22.04   21.81   21.91   21.91   21.51   21.34
   23.43   24.27
       0       0       0       0   20.29   20.06   20.16       0       0       0
       0       0
Pier Skew, UpSta & Num, DnSta & Num=  ,1189.4, 2 ,1189.93, 2 , 0 , 0 , 0 ,,
     1.5     1.5
       0      23
     1.5     1.5
       0      23
Pier Skew, UpSta & Num, DnSta & Num=  ,1212.9, 2 ,1213.43, 2 , 0 , 0 , 0 ,,
     1.5     1.5
       0      23
     1.5     1.5
       0      23
BR Coef=-1 , 1 , 1 ,1.25, 0 ,,,.8,-1,2,0,
WSPro=,,,, 1 ,,,, 0 ,,,, 0 ,,,,-1 ,-1 ,-1 , 0 , 0 , 0 , 0 , 0
BC Design=,, 0 ,, 0 ,,,,,,

Type RM Length L Ch R = 1 ,7806.521,91.67,88.08,84.48
BEGIN DESCRIPTION:
7806.521: Ground data shifted -14.5 ft.
END DESCRIPTION:
XS GIS Cut Line= 6
     3203752.364    13859056.383     3203225.199     13858046.36
     3203215.051    13858040.872     3203060.716    13857957.398
     3202289.592    13857447.466     3201169.819    13857346.912
#Sta/Elev= 30
   -14.5   28.29  426.99   27.74  596.19   26.19  630.03   27.37  731.55   25.34
  748.47   26.06  833.07   25.95 1019.19   24.72  1038.8   25.65 1086.87   24.35
 1103.79   21.15 1120.71   22.51 1129.65   21.77 1176.26   17.25 1192.14   14.07
 1202.06   10.06 1262.03   21.34 1269.37   21.47 1497.46   26.03 1750.27   27.22
 1876.15   26.38 1894.13   27.22 2095.73   28.27 2341.31   27.18 2672.64   28.11
 2784.67   27.13 2823.24   27.66  2834.3   26.66 2883.48   27.99 3360.58   27.95
#Mann= 3 ,-1 , 0
   -14.5     .12       0 1129.65     .06       0 1269.37     .12       0
#XS Ineff= 2 , 0
   -14.5 1162.45   21.17 1238.96   -14.5   21.04
Permanent Ineff=
       F       F
Bank Sta=1129.65,1269.37
XS Rating Curve= 0
Exp/Cntr=.5,.3

Type RM Length L Ch R = 1 ,7718.443,656.91,668.83,679.47
BEGIN DESCRIPTION:
7718.443
END DESCRIPTION:
XS GIS Cut Line= 6
     3203932.595    13858956.884       3203308.3    13857969.952
     3203167.819    13857923.524     3203070.621    13857937.202
     3202299.497     13857427.27     3201179.724    13857326.716
#Sta/Elev= 30
       0   27.93  309.88   27.05  322.86   28.04  416.38   28.24  806.85   25.41
 1144.09   25.27 1213.41      24 1247.33   18.21 1260.81   13.61 1268.15   12.88
 1278.42    9.23 1295.13   12.92  1341.7   15.14 1353.96    16.9 1408.09   21.18
 1468.61   23.67 1656.09   26.44 1792.31   26.08 1921.55   27.14 1972.14   25.86
 1990.12   26.85 2008.11   26.33 2169.95   28.13 2528.66   27.34  2787.6   28.07
 2935.29   27.97 2950.35   26.14 2965.41   27.58 2986.16   27.94 3462.68   28.21
#Mann= 3 ,-1 , 0
       0     .12       0 1247.33     .06       0 1353.96     .12       0
Bank Sta=1247.33,1353.96
XS Rating Curve= 0
Exp/Cntr=.3,.1

Type RM Length L Ch R = 1 ,7049.610,1959.1,1944.97,1931.2
BEGIN DESCRIPTION:
7049.610
END DESCRIPTION:
XS GIS Cut Line= 6
     3204277.614    13858676.747     3203606.668    13857599.682
     3203568.221    13857565.602     3203461.123    13857470.671
      3202046.34    13857025.597     3201165.014    13856948.124
#Sta/Elev= 30
       0   28.25  261.25   28.65  490.99   26.67  508.67      28  544.01   26.48
  650.04   27.07  897.46   25.06 1162.54    25.7 1268.95   24.18 1298.67   22.75
 1320.33   13.75 1405.33   10.13 1415.53    3.18 1417.71    2.98 1420.87    3.32
 1425.67    8.96  1435.6    9.99 1448.67    14.3 1464.46   19.46 1496.07   22.54
 1763.39   26.13 2062.16    26.4 2093.61   27.62 2203.68   27.72 2266.58   26.79
 2360.93   27.63 3108.55   27.64  3123.6   26.55 3153.72   27.71 3831.31   27.51
#Mann= 3 ,-1 , 0
       0     .12       0 1320.33     .06       0 1448.67     .12       0
Bank Sta=1320.33,1448.67
XS Rating Curve= 0
Exp/Cntr=.3,.1

Type RM Length L Ch R = 1 ,5104.642,608.94,617.88,626.47
BEGIN DESCRIPTION:
5104.642
END DESCRIPTION:
XS GIS Cut Line= 6
     3205159.294    13856855.012     3204966.263    13856654.677
      3203550.14    13856170.522     3203318.406    13856182.047
     3201440.927     13856522.49     3201131.805     13856500.67
#Sta/Elev= 30
       0   26.85   490.9   27.57  807.95   24.09 1045.74   28.02 1410.34   25.22
 1442.05   27.19 1679.83   23.12 1743.24   15.72 1758.13   11.73 1774.27    4.39
  1819.9    -.53 1828.51    1.68  1832.3    4.74 1888.43    7.85 1927.33   12.44
 1945.32   10.09 1984.67   20.92 2006.82   23.08 2024.02      28 2030.61   24.83
 2091.59    26.6 2137.32   24.93 2188.65   26.43 2201.56   24.78 2228.79   26.45
 2777.59   25.08 3097.73   27.65  3189.2   26.21 3829.47   28.25 4224.81   27.45
#Mann= 3 ,-1 , 0
       0     .12       0 1758.13     .06       0 1927.33     .12       0
Bank Sta=1758.13,1927.33
XS Rating Curve= 0
Exp/Cntr=.3,.1

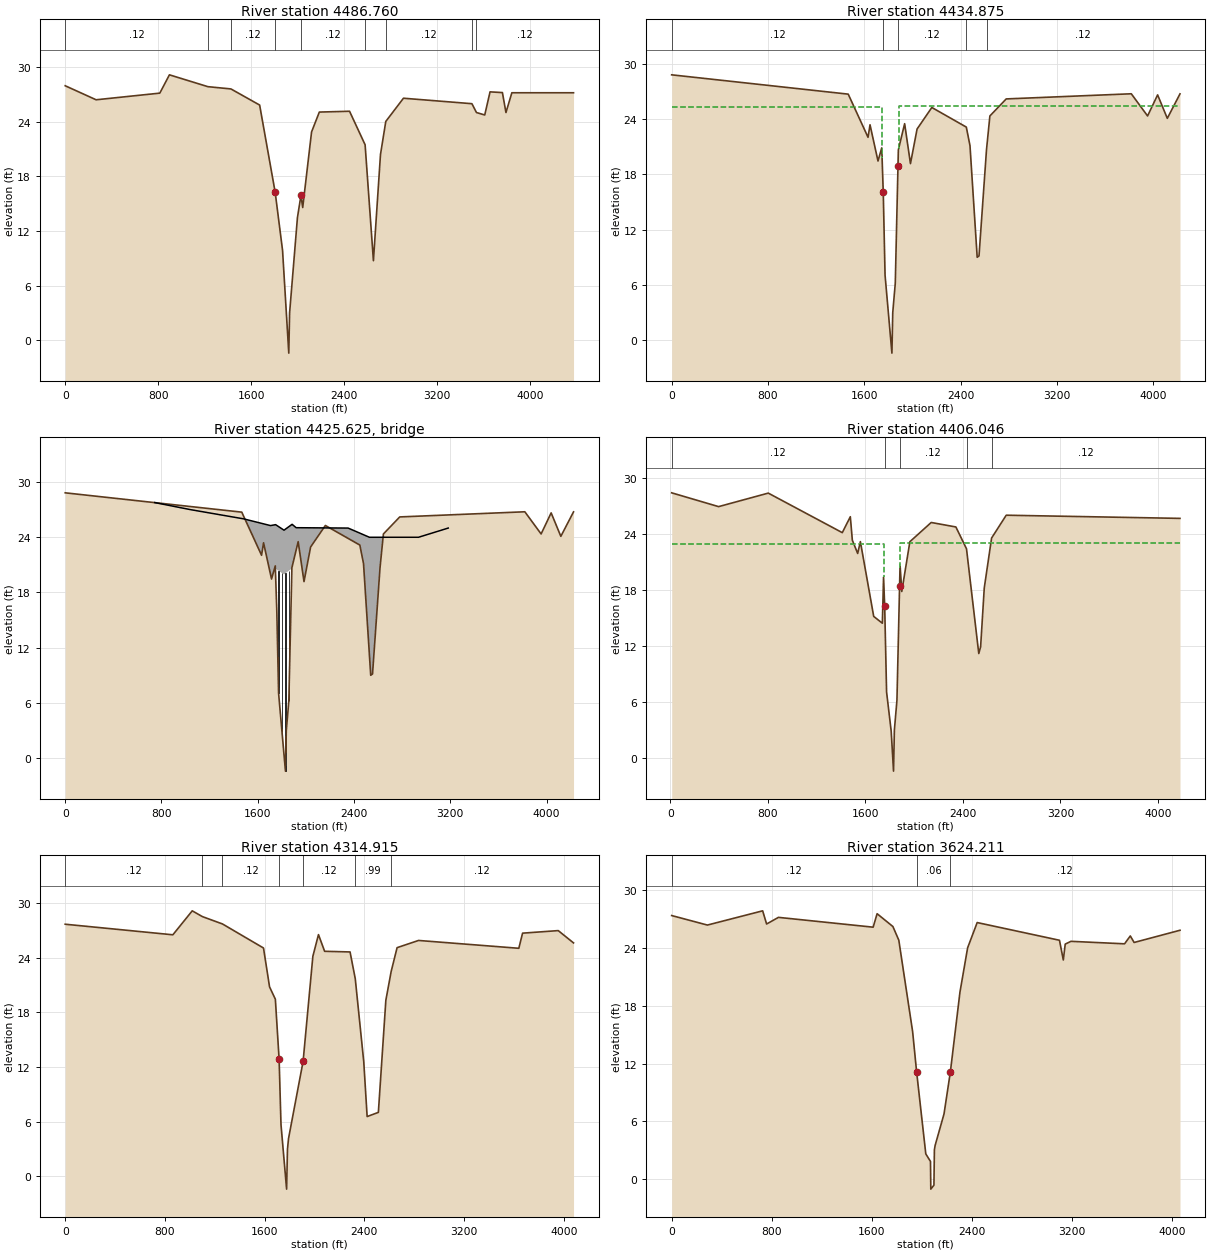
Type RM Length L Ch R = 1 ,4486.760,51.89,51.88,51.88
BEGIN DESCRIPTION:
4486.760
END DESCRIPTION:
XS GIS Cut Line= 6
      3205230.09    13856526.688     3204905.411    13856274.243
     3203646.343    13855686.388     3203446.694    13855614.782
      3201668.36    13855916.534     3201109.857    13855877.183
#Sta/Elev= 30
       0   27.94  266.12    26.4  814.55   27.13  897.32   29.14 1228.41   27.84
 1427.06   27.59 1674.09   25.82 1807.72   16.25  1871.3    9.87 1924.96   -1.42
 1931.88    2.98 1999.52   13.47 2029.85    15.9 2044.92   14.57 2121.14   22.87
    2188   25.05 2448.15   25.14 2582.09   21.46 2653.64    8.73  2714.5   20.39
 2760.14   24.02 2912.28   26.57 3501.74   25.97 3540.76      25 3612.15   24.73
 3657.79   27.27 3764.29   27.19 3794.72      25  3845.6   27.17 4376.56   27.17
#Mann= 9 ,-1 , 0
       0     .12       0 1228.41     .99       0 1427.06     .12       0
 1807.72     .06       0 2029.85     .12       0 2582.09     .99       0
 2760.14     .12       0 3501.74     .99       0 3540.76     .12       0
Bank Sta=1807.72,2029.85
XS Rating Curve= 0
Exp/Cntr=.5,.3

Type RM Length L Ch R = 1 ,4434.875,28.83,28.83,28.83
BEGIN DESCRIPTION:
4434.875
END DESCRIPTION:
XS GIS Cut Line= 6
       3205216.2    13856335.706     3205066.129    13856243.337
     3204676.866    13856094.785     3203462.349    13855565.409
     3201769.948    13855729.787     3201166.258    13855689.383
#Sta/Elev= 30
       0   28.83 1467.05   26.73  1631.6   22.04 1648.05    23.4 1714.45   19.46
  1745.5   20.89 1758.11   16.04 1773.01    7.06 1830.03   -1.42 1836.95    2.98
 1857.98    6.18  1880.5   18.92 1880.52   18.93 1883.51   20.68 1935.73   23.52
 1984.18   19.18 2039.12   22.94 2161.79   25.28 2448.13   23.15 2478.69   21.14
 2538.55       9 2553.62    9.14 2616.05   20.71 2644.05   24.36 2779.68   26.21
 3819.06   26.77 3954.36   24.36 4037.75   26.65 4118.31    24.1 4223.71   26.76
#Mann= 5 ,-1 , 0
       0     .12       0 1758.11     .06       0  1880.5     .12       0
 2448.13     .99       0 2616.05     .12       0
#XS Ineff= 2 , 0
       0 1748.22   25.37  1885.3       0   25.41
Permanent Ineff=
       F       F
Bank Sta=1758.11,1880.52
XS Rating Curve= 0
Exp/Cntr=.5,.3

Type RM Length L Ch R = 3 ,4425.625,,,
BEGIN DESCRIPTION:
U.P.R.R.
END DESCRIPTION:
Bridge Culvert--1,0,-1,-1, 0
Deck Dist Width WeirC Skew NumUp NumDn MinLoCord MaxHiCord MaxSubmerge Is_Ogee
1,16.5,2.6,0, 14, 14, , , .95, 0, 0,0,,
     744    1042    1483    1706  1748.2 1748.22  1818.1  1885.3 1885.31  1918.7
  2350.7  2527.7  2935.7  3182.7
   27.77      27      26   25.27   25.37   25.37   24.77   25.41   25.41   25.04
      25      24      24      25
       0       0       0       0       0   20.57   19.97   20.61       0       0
       0       0       0       0
  744.81 1042.81 1483.81 1706.81    1749 1749.03 1818.91 1886.11 1886.12 1919.51
 2351.51 2528.51 2936.51 3183.51
      28      27      26   25.27   25.37   25.37   24.77   25.41   25.41   25.04
      25      24      24      25
       0       0       0       0       0   20.57   19.97   20.61       0       0
       0       0       0       0
Pier Skew, UpSta & Num, DnSta & Num=  ,1773.22, 2 ,1774.03, 2 , 0 , 0 , 0 ,,
     2.4     2.4
       0      23
     2.4     2.4
       0      23
Pier Skew, UpSta & Num, DnSta & Num=  ,1801.2, 2 ,1802.01, 2 , 0 , 0 , 0 ,,
     2.4     2.4
       0      23
     2.4     2.4
       0      23
Pier Skew, UpSta & Num, DnSta & Num=  ,1830, 2 ,1830.81, 2 , 0 , 0 , 0 ,,
     2.4     2.4
       0      23
     2.4     2.4
       0      23
Pier Skew, UpSta & Num, DnSta & Num=  ,1857.8, 2 ,1858.61, 2 , 0 , 0 , 0 ,,
     2.4     2.4
       0      23
     2.4     2.4
       0      23
BR Coef=-1 , 1 , 1 ,1.05, 0 ,,,.8,-1,1.2,0,
WSPro=,,,, 1 ,,,, 0 ,,,, 0 ,,,,-1 ,-1 ,-1 , 0 , 0 , 0 , 0 , 0
BC Design=,, 0 ,, 0 ,,,,,,

Type RM Length L Ch R = 1 ,4406.046,96.53,91.13,85.73
BEGIN DESCRIPTION:
4406.046: Ground data shifted by 11.2 ft.
END DESCRIPTION:
XS GIS Cut Line= 6
     3205214.165    13856307.721     3205072.645    13856223.526
     3203670.909    13855609.749      3203471.26    13855538.143
     3201867.377    13855593.022     3201212.903    13855534.065
#Sta/Elev= 30
    11.2   28.42  396.03   26.94  803.45   28.39 1410.55   24.15 1476.47   25.86
 1492.96   23.34 1536.69   21.92 1558.88   23.19 1668.21   15.17 1739.06   14.44
 1749.03   19.39 1758.13   16.31 1773.81    7.06 1811.49    2.88 1830.84   -1.42
 1837.76    2.98 1858.78    6.18 1880.52   18.48 1884.31   20.68 1898.41   17.84
 1964.87   23.18 2139.71   25.24 2342.19   24.76 2429.26   22.42 2529.94   11.19
 2544.95    11.9 2574.96   18.22    2635   23.57 2755.07   26.02 4180.27   25.68
#Mann= 5 ,-1 , 0
    11.2     .12       0 1758.13     .06       0 1880.52     .12       0
 2429.26     .99       0    2635     .12       0
#XS Ineff= 2 , 0
    11.2 1749.03   22.97 1886.11    11.2   23.01
Permanent Ineff=
       F       F
Bank Sta=1758.13,1880.52
XS Rating Curve= 0
Exp/Cntr=.5,.3

Type RM Length L Ch R = 1 ,4314.915,684.87,690.71,696.54
BEGIN DESCRIPTION:
4314.915
END DESCRIPTION:
XS GIS Cut Line= 6
     3205213.663    13856128.297     3204822.867    13855949.721
      3203679.65    13855492.142      3203468.27     13855474.65
     3201952.402     13855408.92     3201267.726    13855351.518
#Sta/Elev= 30
       0   27.67   863.6   26.51 1019.01   29.14 1099.83   28.51 1261.46    27.7
 1590.66   25.06 1639.14    20.8 1685.79   19.44 1715.89   12.85 1730.94    5.69
 1775.99   -1.39 1782.83    2.97 1791.15    4.14 1908.33   12.63 1986.53   24.15
 2031.58   26.53 2080.98    24.7    2285   24.63 2326.74   21.69 2394.87   12.58
 2421.94    6.57 2512.03    7.03 2572.08   19.33 2614.59   22.48 2662.17    25.1
 2834.32   25.89 3638.72   25.03 3668.82   26.69 3954.82   26.97 4077.53   25.62
#Mann= 7 ,-1 , 0
       0     .12       0 1099.83     .99       0 1261.46     .12       0
 1715.89     .06       0 1908.33     .12       0 2326.74     .99       0
 2614.59     .12       0
Bank Sta=1715.89,1908.33
XS Rating Curve= 0
Exp/Cntr=.3,.1

Type RM Length L Ch R = 1 ,3624.211,1011.92,1014.23,1016.55
BEGIN DESCRIPTION:
3624.211
END DESCRIPTION:
XS GIS Cut Line= 6
     3205456.644    13855492.519     3203624.626    13854899.337
      3203491.27    13854852.064     3203490.492    13854851.789
     3203353.461    13854803.213     3201540.462    13854443.376
#Sta/Elev= 30
       0   27.39  285.53    26.4     727   27.88  758.53   26.51  853.13    27.2
 1609.93   26.18 1641.46   27.58  1767.6   26.25  1814.9   24.83 1925.26   15.33
 1957.09   11.15 2030.59    2.61 2068.04    1.83 2070.56   -1.05 2095.55    -.64
 2099.31    3.04 2105.08    3.49 2176.22    6.77 2227.08   11.15 2303.54   19.43
 2364.71   24.03 2441.18   26.66 3098.76   24.82 3129.34   22.77 3144.63   24.42
 3190.51   24.71  3618.7   24.45 3664.58   25.27 3695.17   24.59 4061.72   25.86
#Mann= 3 ,-1 , 0
       0     .12       0 1957.09     .06       0 2227.08     .12       0
Bank Sta=1957.09,2227.08
XS Rating Curve= 0
Exp/Cntr=.3,.1