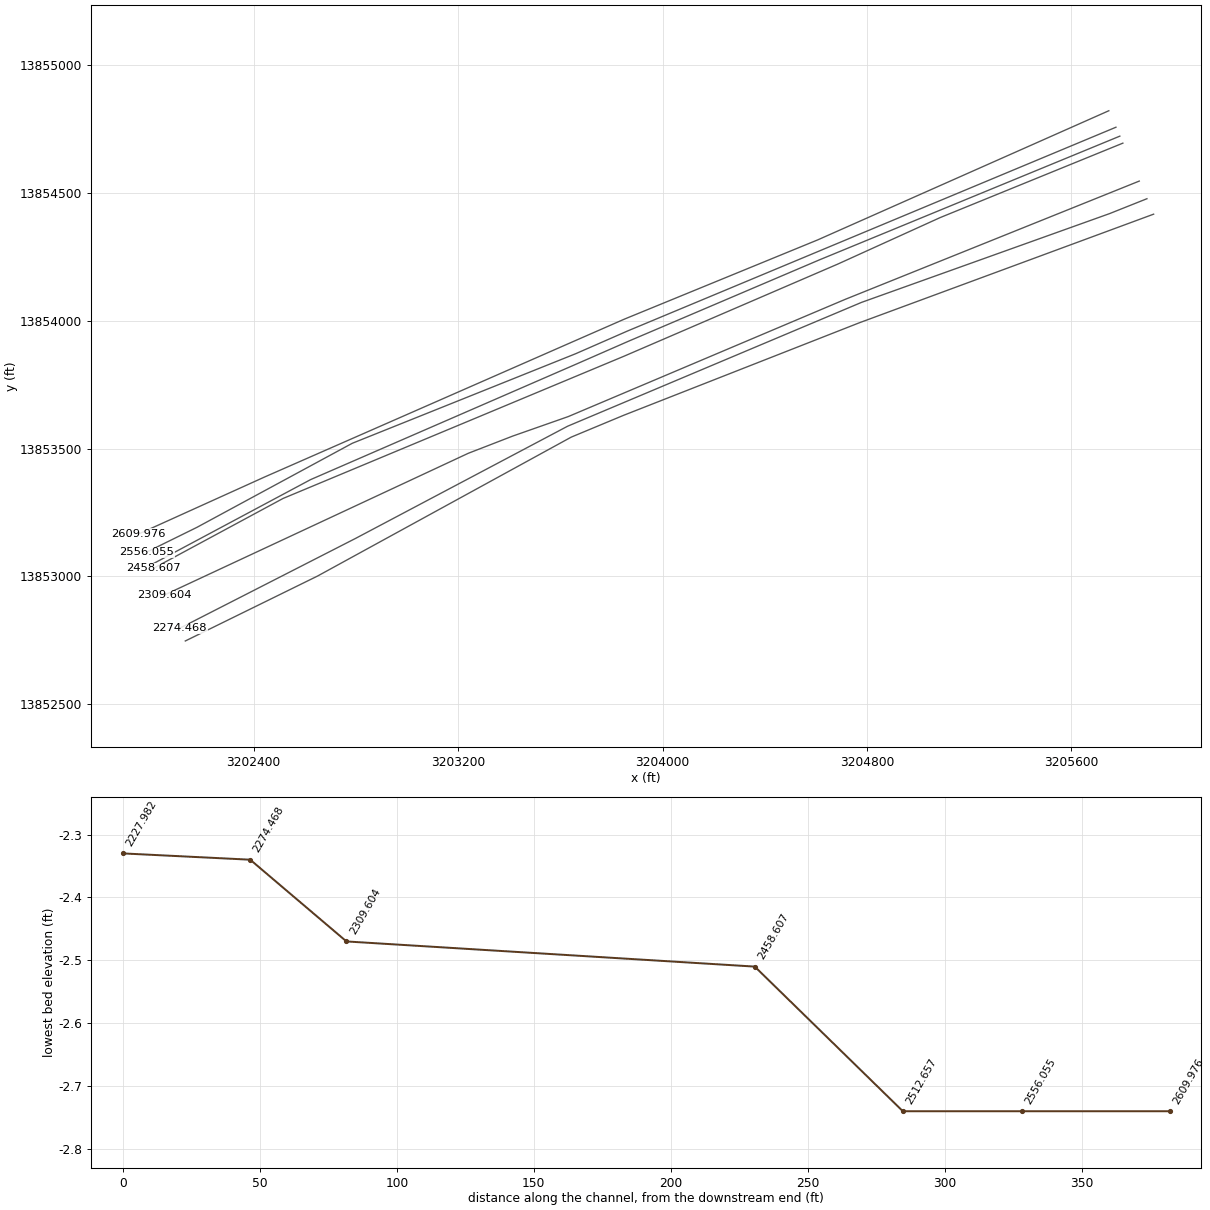
HEC-RAS study G103-01-00.prj: G103-01-00

--- G103-01-00.g10 (geometry) --- (continued)

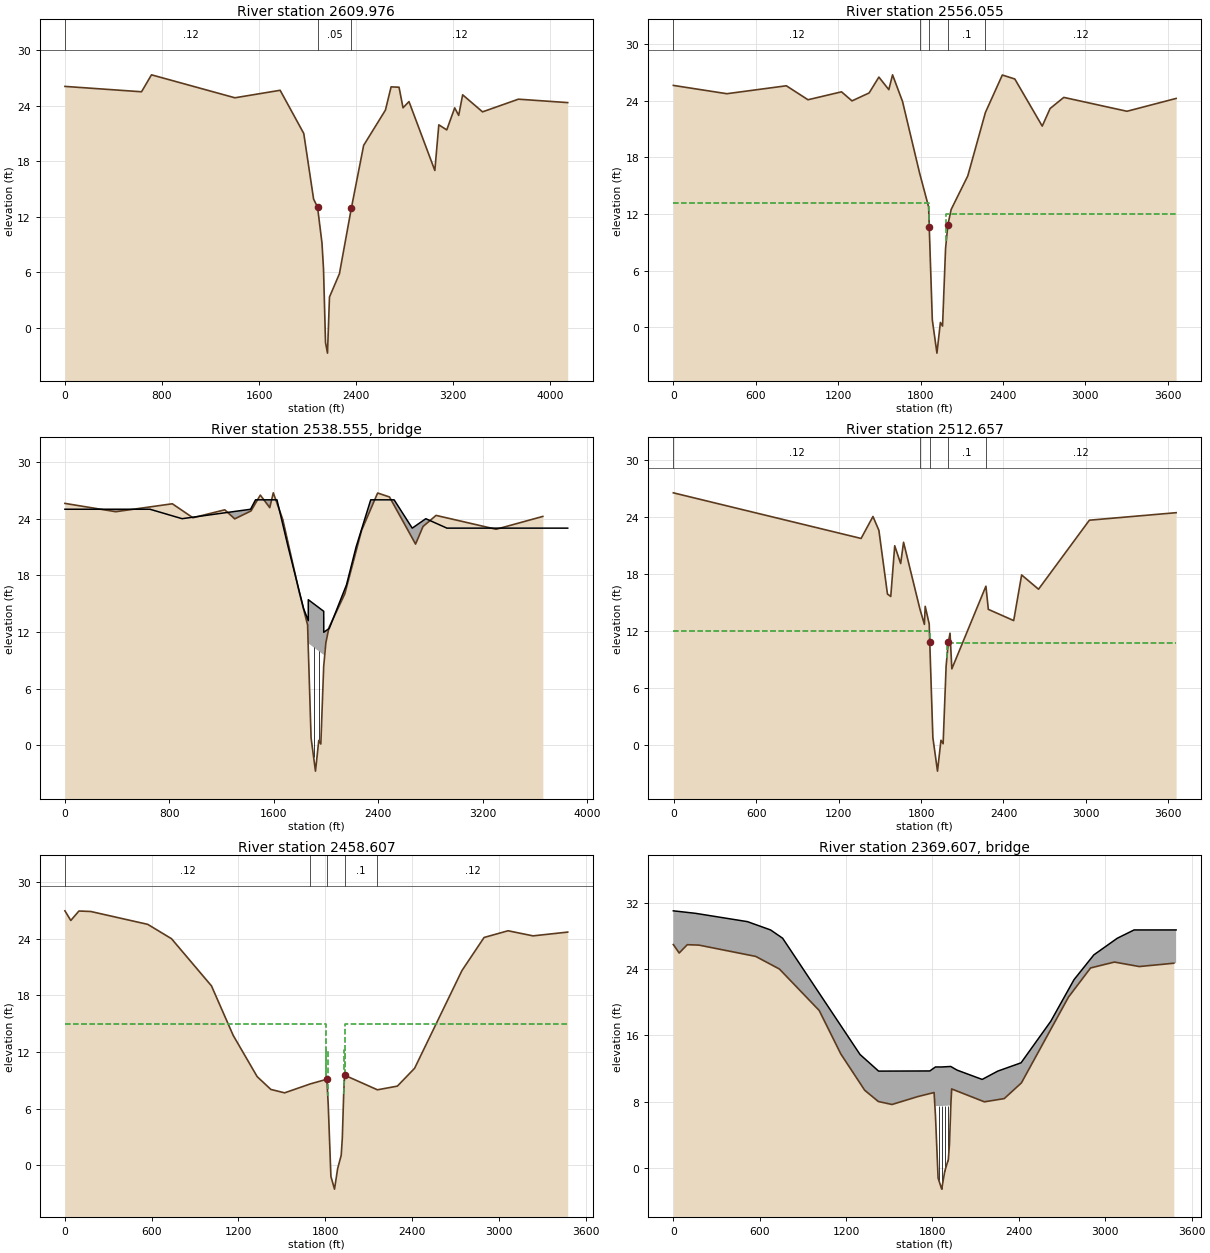
Type RM Length L Ch R = 1 ,2609.976,53.92,53.92,53.92
BEGIN DESCRIPTION:
2609.976
END DESCRIPTION:
XS GIS Cut Line= 6
     3205746.964     13854822.25     3204607.257    13854316.615
     3203850.851    13854006.588     3203647.526    13853917.522
     3202442.163    13853388.479     3201949.872    13853165.704
#Sta/Elev= 30
       0   26.07   631.2   25.49  713.25   27.32 1400.58   24.84 1773.43   25.65
 1967.96   20.99 2049.02    13.9 2081.62   13.03 2118.11    9.16 2130.74    6.37
 2147.31    -1.6 2163.58   -2.74 2179.87    3.32 2261.75    5.83 2360.03   12.91
 2461.47    19.7 2640.91   23.51 2687.66   26.02 2753.18   25.98 2785.94   23.76
 2835.09   24.43 3048.04   16.99 3080.81   21.92 3146.33   21.37 3211.86   23.75
 3244.62   22.94 3277.38   25.16 3441.19   23.32 3736.73   24.69 4142.99   24.32
#Mann= 3 ,-1 , 0
       0     .12       0 2081.62     .05       0 2360.03     .12       0
Bank Sta=2081.62,2360.03
XS Rating Curve= 0
Exp/Cntr=.5,.3

Type RM Length L Ch R = 1 ,2556.055,43.36,43.4,44.08
BEGIN DESCRIPTION:
2556.055
END DESCRIPTION:
XS GIS Cut Line= 6
     3205774.905    13854757.741     3203863.485    13853960.278
     3203660.159    13853871.212     3202785.961    13853520.709
     3202177.703    13853191.603     3201980.781    13853094.689
#Sta/Elev= 30
       0   25.62 389.504   24.74 822.748   25.58 980.425    24.11224.569   24.94
1300.776   23.981425.457   24.821496.596    26.51568.945   25.171596.069   26.74
1668.691   23.921792.922   16.34 1858.87   12.741863.293   10.63 1885.57     .78
1919.219   -2.741944.365     .511960.117     .131982.058    8.341998.737   10.85
2022.868   12.482143.735   16.032272.151   22.752395.304   26.722486.195    26.3
2685.962   21.312743.035   23.172842.915   24.353302.895   22.883660.692   24.24
#Mann= 5 ,-1 , 0
       0     .12       01792.922      .1       01863.293     .05       0
1998.737      .1       02272.151     .12       0
#XS Ineff= 2 , 0
       0 1862.94    13.2 1987.38       0   11.97
Permanent Ineff=
       F       F
Bank Sta=1863.293,1998.737
XS Rating Curve= 0
Skew Angle= 28
Exp/Cntr=.5,.3

Type RM Length L Ch R = 3 ,2538.555,,,
BEGIN DESCRIPTION:
IH 10 Westbound Feeder
Bridge deck data manually skewed 28 degrees.
END DESCRIPTION:
Bridge Culvert--1,0,-1,-1, 0
Deck Dist Width WeirC Skew NumUp NumDn MinLoCord MaxHiCord MaxSubmerge Is_Ogee
1,33,2.6,0, 22, 23, , , .95, 0, 0,0,,
       0  651.35  897.52 1421.99 1459.95 1624.18 1709.83 1828.14 1864.08 1864.17
 1982.48 1982.57 2024.86 2156.86 2230.24 2342.37 2521.61 2660.32 2764.42    2926
 3190.88 3851.33
      25      25      24      25      26      26      21   14.48    13.2   15.42
   14.19   11.97   12.38      17      21      26      26      23      24      23
      23      23
       0       0       0       0       0       0       0    10.8    10.8    10.8
    9.57    9.57    9.57       0       0       0       0       0       0       0
       0       0
       0  651.86  898.03  1422.5 1460.46 1624.69 1710.34 1828.65 1864.59 1864.68
 1982.99 1983.08    1990 2025.37 2157.37 2230.75 2342.88 2522.12 2660.83 2764.93
 2926.51 3191.39 3851.84
      25      25      24      25      26      26      21   14.48    13.2   15.42
   14.19   11.97   12.04   12.38      17      21      26      26      23      24
      23      23      23
       0       0       0       0       0       0       0    10.8    10.8    10.8
    9.57    9.57    9.57       0       0       0       0       0       0       0
       0       0       0
Pier Skew, UpSta & Num, DnSta & Num=  ,1904.783, 2 ,1905.291, 2 , 0 , 0 , 0 ,,
    1.01    1.01
       0      12
    1.01    1.01
       0      12
Pier Skew, UpSta & Num, DnSta & Num=  ,1944.516, 2 ,1945.024, 2 , 0 , 0 , 0 ,,
    1.01    1.01
       0      12
    1.01    1.01
       0      12
BR Coef=-1 , 1 , 1 ,1.25, 0 ,,,.8,-1,2,0,
WSPro=,,,, 1 ,,,, 0 ,,,, 0 ,,,,-1 ,-1 ,-1 , 0 , 0 , 0 , 0 , 0
BC Design=,, 0 ,, 0 ,,,,,,

Type RM Length L Ch R = 1 ,2512.657,53.83,54.05,53.63
BEGIN DESCRIPTION:
2512.657: Ground data shifted by -3.2 ft.
END DESCRIPTION:
XS GIS Cut Line= 6
     3205790.037    13854722.806     3204613.292    13854238.167
      3203866.81    13853920.049     3203663.485    13853830.984
     3202622.647    13853378.434     3202001.684    13853046.664
#Sta/Elev= 30
    -3.2   26.54 1363.58   21.74 1449.96   24.05 1493.15   22.59 1555.52   15.89
 1579.53   15.64 1608.32   20.97 1651.51    19.1 1672.63   21.34    1792    14.3
 1824.27    12.7 1830.18    14.6 1859.38   12.74 1863.33   10.85 1886.08     .78
 1919.73   -2.74 1944.87     .51 1960.62     .14 1982.57    8.34 1998.23   10.77
 1998.74   10.82 2010.96   11.77 2024.08    8.02 2272.17   16.72 2289.75   14.28
 2474.35    13.1 2532.12    17.9 2655.12    16.4 3025.18   23.66 3656.66   24.45
#Mann= 5 ,-1 , 0
    -3.2     .12       0    1792      .1       0 1863.33     .04       0
 1998.23      .1       0 2272.17     .12       0
#XS Ineff= 2 , 0
    -3.2 1863.44      12 1987.89    -3.2   10.77
Permanent Ineff=
       F       F
Bank Sta=1863.33,1998.74
XS Rating Curve= 0
Skew Angle= 28
Exp/Cntr=.5,.3

Type RM Length L Ch R = 1 ,2458.607,150.02,149,147.63
BEGIN DESCRIPTION:
2458.607
END DESCRIPTION:
XS GIS Cut Line= 6
     3205801.914    13854695.385     3205086.999    13854404.115
     3204685.916    13854221.975     3203848.437    13853861.028
      3202514.91    13853304.719     3202008.271    13853031.531
#Sta/Elev= 30
       0   26.94  40.541   25.92  96.825   26.92 178.679   26.87 572.267   25.51
 736.906   23.991013.106      191163.731   13.751329.385    9.391423.836    8.04
1518.841    7.681697.637    8.631811.126    9.121820.653    6.371838.986   -1.17
 1863.97   -2.511885.491    -.341910.156    1.071917.838    2.891927.777    7.76
1933.471    9.561936.272    9.532160.759       82298.419    8.392417.686   10.28
2744.675   20.612898.034   24.123063.697   24.833236.396   24.293476.248   24.69
#Mann= 5 ,-1 , 0
       0     .12       01697.637      .1       01811.126     .04       0
1936.272      .1       02160.759     .12       0
#XS Ineff= 4 ,-1
       0 1807.36      15 1807.36 1817.36    12.2 1927.26 1937.26    12.2
 1937.26 3476.25      15
Permanent Ineff=
       F       F       F       F
Bank Sta=1811.126,1936.272
XS Rating Curve= 0
Skew Angle= 33
Exp/Cntr=.5,.3

Type RM Length L Ch R = 3 ,2369.607,,,
BEGIN DESCRIPTION:
IH 10 Mainlanes
END DESCRIPTION:
Bridge Culvert--1,0,-1,-1, 0
Deck Dist Width WeirC Skew NumUp NumDn MinLoCord MaxHiCord MaxSubmerge Is_Ogee
1,122,2.6,33, 21, 22, , , .95, 0, 0,0,,
       0  153.81  514.36  675.38  759.25 1296.84 1425.74 1781.59 1820.59 1867.13
 1926.68 1970.71 2145.15 2253.34  2415.2 2621.52 2782.54 2920.92 3083.62 3200.37
 3492.23
      31    30.7    29.7    28.7    27.7    13.7    11.7   11.72    12.2    12.2
   12.26   11.82    10.7    11.7    12.7    17.7    22.7    25.7    27.7    28.7
    28.7
       0       0       0       0       0       0       0    7.02     7.5     7.5
    7.56    7.12       0       0       0       0       0       0       0       0
       0
   -51.7    1.14  154.95  515.49  676.52  760.39 1297.97 1426.88 1782.72 1821.72
 1868.27 1927.81 1971.84 2146.29 2254.48 2416.34 2622.65 2783.68 2922.06 3084.76
  3201.5 3493.36
      31      31    30.7    29.7    28.7    27.7    13.7    11.7   11.72    12.2
    12.2   12.26   11.82    10.7    11.7    12.7    17.7    22.7    25.7    27.7
    28.7    28.7
       0       0       0       0       0       0       0       0    7.02     7.5
     7.5    7.56    7.12       0       0       0       0       0       0       0
       0       0
Pier Skew, UpSta & Num, DnSta & Num=  ,1843.23, 2 ,1844.37, 2 , 0 , 0 , 0 ,,
     .99     .99
       0      10
     .99     .99
       0      10
Pier Skew, UpSta & Num, DnSta & Num=  ,1864.197, 2 ,1865.334, 2 , 0 , 0 , 0 ,,
     .99     .99
       0      10
     .99     .99
       0      10
Pier Skew, UpSta & Num, DnSta & Num=  ,1885.164, 2 ,1886.3, 2 , 0 , 0 , 0 ,,
     .99     .99
       0      10
     .99     .99
       0      10
Pier Skew, UpSta & Num, DnSta & Num=  ,1906.13, 2 ,1907.267, 2 , 0 , 0 , 0 ,,
     .99     .99
       0      10
     .99     .99
       0      10
BR Coef=-1 , 1 , 1 ,1.25, 0 ,,,.8,-1,2,0,
WSPro=,,,, 1 ,,,, 0 ,,,, 0 ,,,,-1 ,-1 ,-1 , 0 , 0 , 0 , 0 , 0
BC Design=,, 0 ,, 0 ,,,,,,

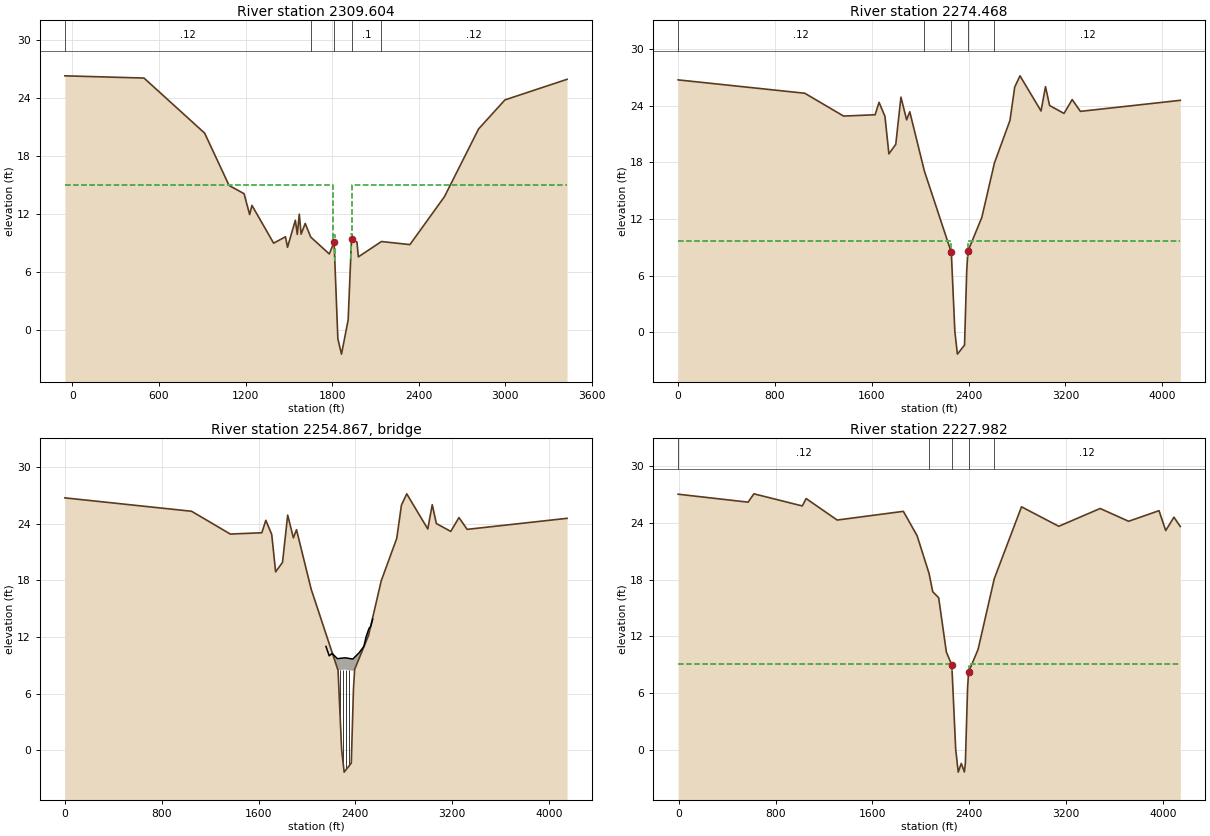
Type RM Length L Ch R = 1 ,2309.604,35.5,35.14,35.14
BEGIN DESCRIPTION:
2309.604: Ground data shift -51.7 ft.
END DESCRIPTION:
XS GIS Cut Line= 6
       3205866.2    13854546.968     3204715.878    13854084.287
     3203631.257    13853625.195     3203413.481    13853548.741
     3203239.557    13853481.345     3202049.415    13852926.212
#Sta/Elev= 30
   -51.7   26.32  496.29   26.09  916.63   20.39 1085.74   14.98 1189.42   14.13
 1228.33   11.97  1244.1   12.92 1394.45    9.01 1476.46    9.67 1490.64    8.58
  1544.8   11.38 1558.47    9.92 1572.14   12.01 1584.82    9.94 1613.15   11.05
  1651.5    9.64 1780.18    7.89 1813.29    9.12  1839.5    -.89 1864.64   -2.47
 1910.82    1.08  1934.2    9.49 1971.88    9.11 1981.49    7.59 2141.48    9.18
 2338.57    8.86 2577.62   13.81 2814.59   20.83 2997.02   23.83 3427.31   25.96
#Mann= 5 ,-1 , 0
   -51.7     .12       0  1651.5      .1       0 1813.29     .04       0
  1934.2      .1       0 2141.48     .12       0
#XS Ineff= 4 ,-1
   -51.7 1808.28      15 1808.28 1818.28    9.85 1928.19 1938.19    9.91
 1938.19 3427.32      15
Permanent Ineff=
       F       F       F       F
Bank Sta=1813.29,1934.2
XS Rating Curve= 0
Skew Angle= 33
Exp/Cntr=.5,.3

Type RM Length L Ch R = 1 ,2274.468,46.49,46.49,46.49
BEGIN DESCRIPTION:
2274.468
END DESCRIPTION:
XS GIS Cut Line= 6
     3205896.127    13854477.874      3205750.32    13854419.754
      3204779.24    13854072.218      3203628.39    13853587.296
     3202798.444     13853148.21     3202110.487    13852796.688
#Sta/Elev= 30
       0   26.76 1046.56   25.34 1366.65   22.92 1627.19   23.06 1659.75   24.38
  1708.6   22.89 1741.17   18.91 1797.97   19.92  1840.6   24.93 1887.72   22.52
 1913.61   23.38 2034.27   17.09  2256.9    8.45 2286.08     .07 2307.17   -2.34
 2366.09   -1.38 2384.09     6.5  2393.8    8.56 2508.92   12.17 2613.18   17.95
 2741.49   22.46 2780.44   25.99 2824.19   27.19  2998.1   23.46 3034.98   26.04
 3068.92   24.04 3187.71    23.2 3255.59   24.67 3323.47   23.42 4148.71   24.59
#Mann= 5 ,-1 , 0
       0     .12       0 2034.27      .1       0  2256.9     .04       0
  2393.8      .1       0 2613.18     .12       0
#XS Ineff= 2 , 0
       0 2256.86     9.7  2391.1       0    9.66
Permanent Ineff=
       F       F
Bank Sta=2256.9,2393.8
XS Rating Curve= 0
Exp/Cntr=.5,.3

Type RM Length L Ch R = 3 ,2254.867,,,
BEGIN DESCRIPTION:
IH 10 Eastbound Feeder
END DESCRIPTION:
Bridge Culvert--1,0,-1,-1, 0
Deck Dist Width WeirC Skew NumUp NumDn MinLoCord MaxHiCord MaxSubmerge Is_Ogee
1,37.2,2.6,0, 14, 14, , , .95, 0, 0,0,,
  2156.9  2183.5  2206.8  2208.8  2251.3  2314.3  2378.8  2430.3  2470.2  2488.1
 2512.66 2525.89 2535.92 2542.86
      11      10   10.24   10.24     9.7    9.79    9.66   10.32      11      12
   12.92    13.1   13.56    13.9
       0       0       0       9    8.45    8.54    8.41    8.41       0       0
       0       0       0       0
  2158.9  2185.5  2208.8  2210.8  2253.3  2316.3  2380.8  2432.3  2472.2  2490.1
 2514.66 2525.89 2535.92 2542.86
      11      10   10.24   10.24     9.7    9.79    9.66   10.32      11      12
   12.83    13.1   13.56    13.9
       0       0       0       9    8.45    8.54    8.41    8.41       0       0
       0       0       0       0
Pier Skew, UpSta & Num, DnSta & Num=  ,2273.8, 2 ,2275.8, 2 , 0 , 0 , 0 ,,
     .99     .99
       0       9
     .99     .99
       0       9
Pier Skew, UpSta & Num, DnSta & Num=  ,2299.3, 2 ,2301.3, 2 , 0 , 0 , 0 ,,
     .99     .99
       0       9
     .99     .99
       0       9
Pier Skew, UpSta & Num, DnSta & Num=  ,2324.299, 2 ,2326.3, 2 , 0 , 0 , 0 ,,
     .99     .99
       0       9
     .99     .99
       0       9
Pier Skew, UpSta & Num, DnSta & Num=  ,2349.8, 2 ,2351.8, 2 , 0 , 0 , 0 ,,
     .99     .99
       0       9
     .99     .99
       0       9
BR Coef=-1 , 1 , 1 ,1.25, 0 ,,,.8,-1,2,0,
WSPro=,,,, 1 ,,,, 0 ,,,, 0 ,,,,-1 ,-1 ,-1 , 0 , 0 , 0 , 0 , 0
BC Design=,, 0 ,, 0 ,,,,,,

Type RM Length L Ch R = 1 ,2227.982,135.56,135.48,135.4
BEGIN DESCRIPTION:
2227.982: Ground Data shifted -5.5 ft to match upstream bridge encroachment.
END DESCRIPTION:
XS GIS Cut Line= 6
     3205922.313    13854417.417     3204770.624    13853992.354
     3203847.805    13853630.108     3203642.773    13853544.724
     3202649.751    13853000.906     3202132.188    13852746.829
#Sta/Elev= 30
    -5.5   27.03  572.57   26.19  620.54   27.07 1020.26   25.79 1052.24   26.57
 1308.74    24.3 1855.73   25.22 1969.42   22.64 2067.95   18.66 2098.34   16.73
 2147.53   16.09 2211.14   10.35 2256.16    8.99 2288.12     .08 2309.22   -2.33
 2334.46   -1.41 2359.84   -2.31 2368.13   -1.37 2386.09    6.48 2394.71    8.25
 2472.96   10.63 2607.11   18.11 2832.11    25.7 3139.94   23.64 3481.98   25.52
 3717.33   24.17 3968.54   25.29 4023.68   23.19 4091.76    24.6 4144.34   23.62
#Mann= 5 ,-1 , 0
    -5.5     .12       0 2067.95      .1       0 2256.16    .045       0
 2394.71      .1       0 2607.11     .12       0
#XS Ineff= 2 , 0
    -5.5 2258.78    9.08 2396.74    -5.5    9.04
Permanent Ineff=
       F       F
Bank Sta=2256.16,2394.71
XS Rating Curve= 0
Exp/Cntr=.5,.3