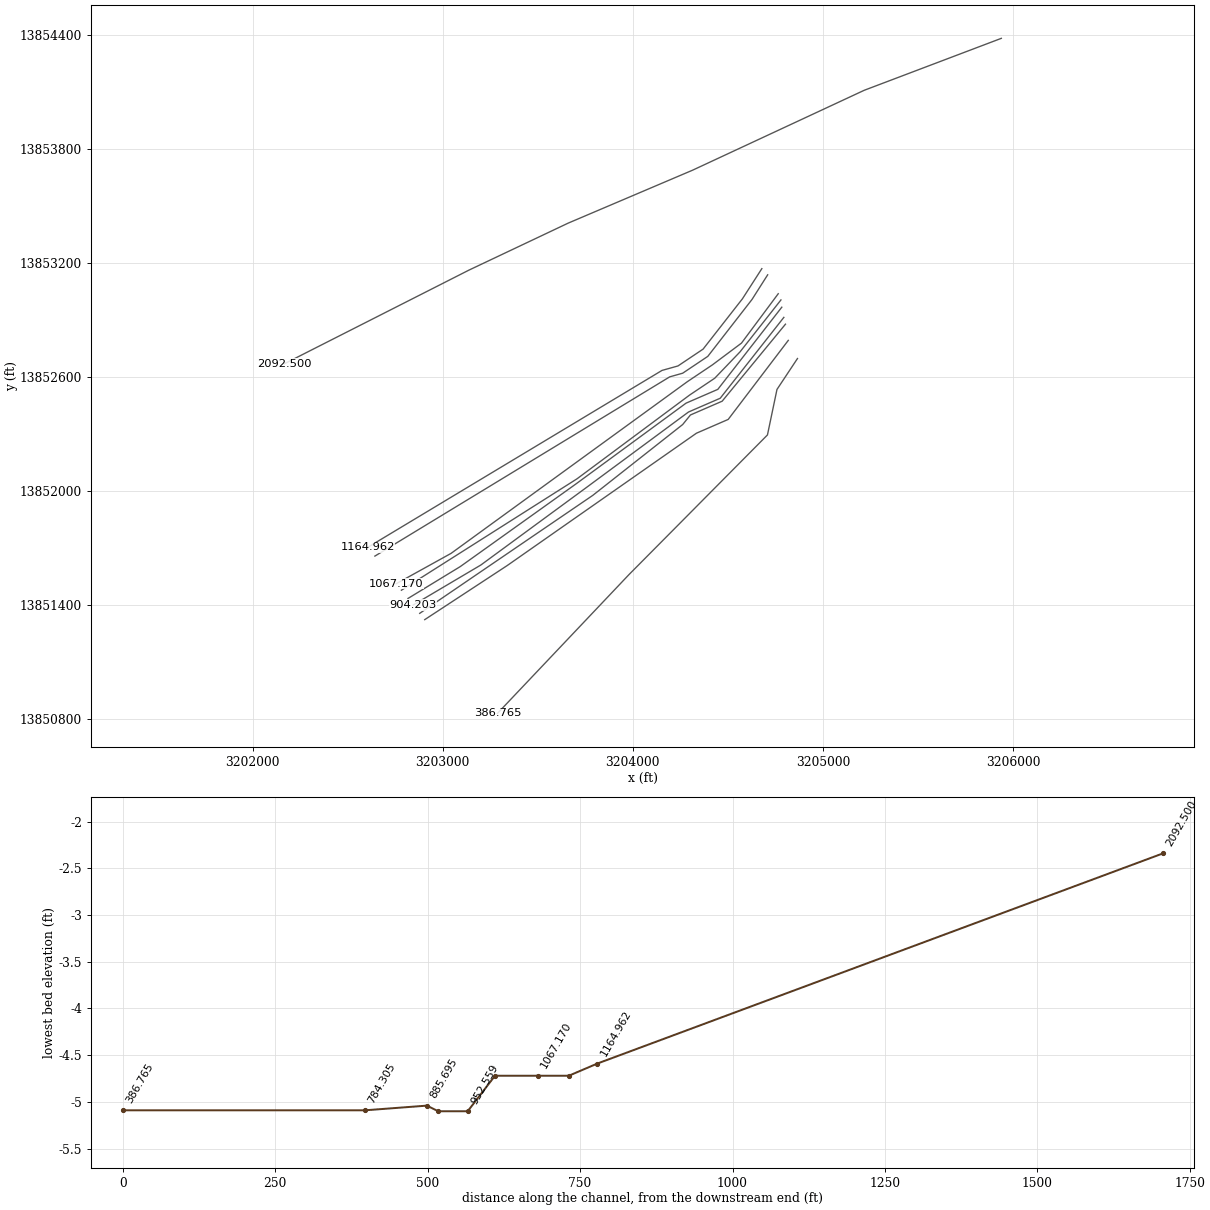
HEC-RAS study G103-01-00.prj: G103-01-00

--- G103-01-00.g10 (geometry) --- (continued)

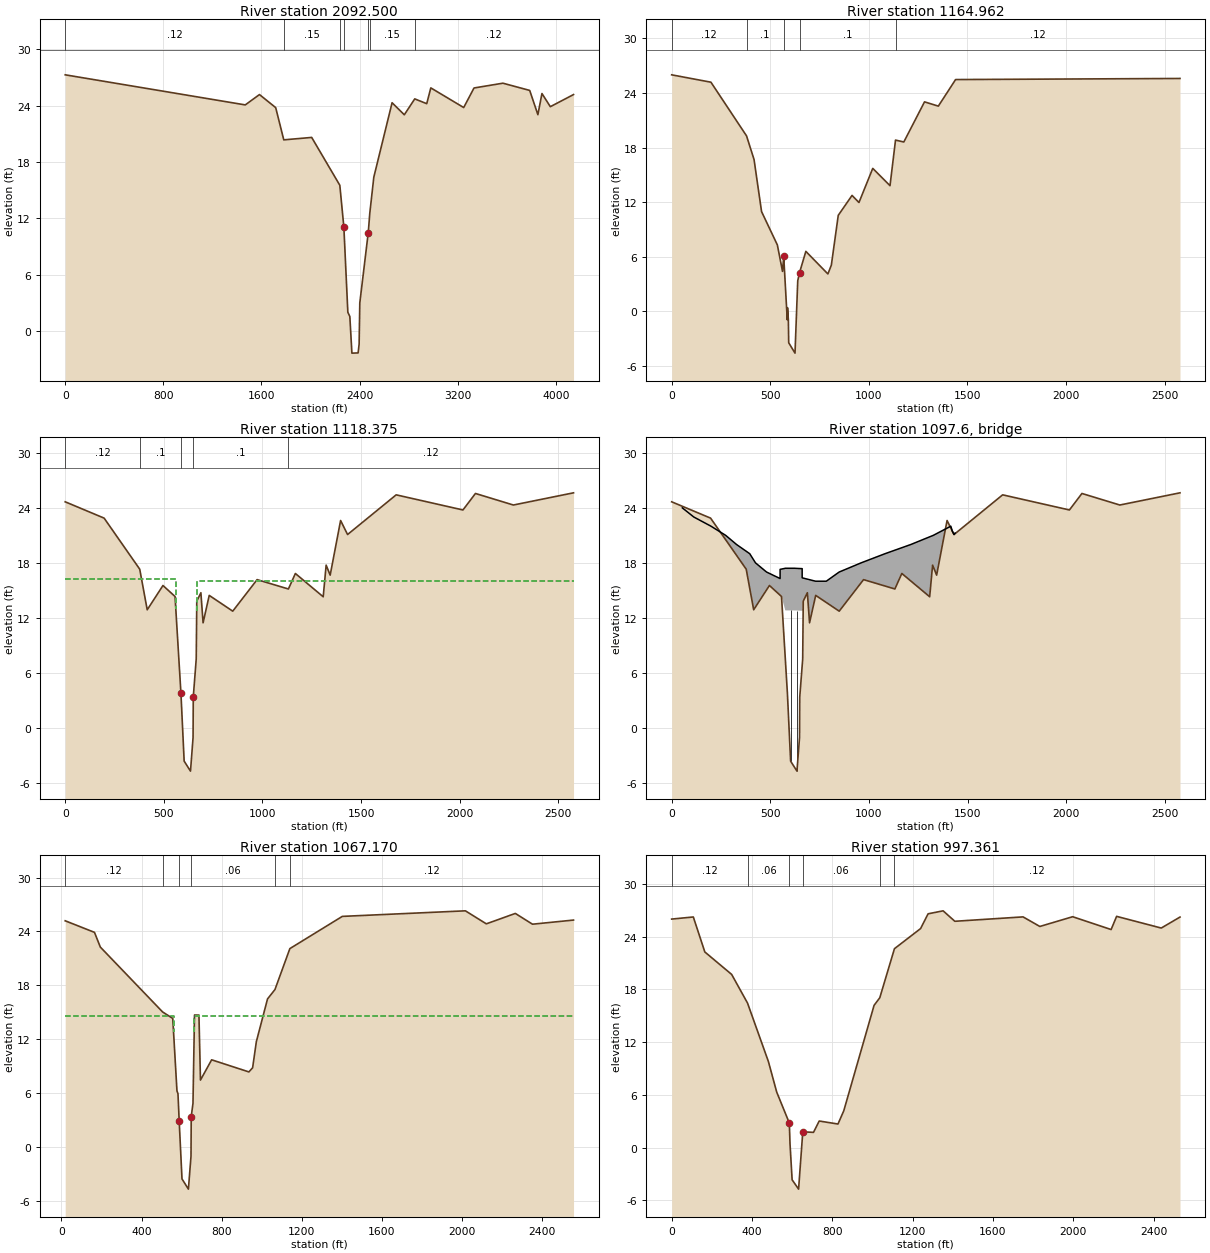
Type RM Length L Ch R = 1 ,2092.500,923.55,927.54,931.59
BEGIN DESCRIPTION:
2092.500
END DESCRIPTION:
XS GIS Cut Line= 6
     3205938.256     13854380.61     3205217.006    13854107.333
     3204314.925    13853687.343     3203660.053    13853408.709
     3203137.319    13853161.147     3202166.288    13852668.484
#Sta/Elev= 30
       0   27.27 1468.43   24.07 1584.26   25.17 1716.62   23.78 1782.49   20.35
 2010.09   20.61 2239.53   15.52 2272.45   11.08 2304.95    2.01  2321.2    1.56
 2338.07   -2.34 2388.68   -2.32 2396.99   -1.38 2402.44       3 2471.42   10.48
 2483.77   12.52 2516.75   16.38 2665.73    24.3 2765.48   23.02 2850.55   24.71
 2948.35    24.2  2981.6   25.88 3249.85   23.79 3333.95   25.87 3569.43   26.38
 3788.09   25.61 3854.81   23.03 3887.96   25.28 3956.29   23.88 4145.48   25.17
#Mann= 7 ,-1 , 0
       0     .12       0 1782.49     .15       0 2239.53      .1       0
 2272.45    .045       0 2471.42      .1       0 2483.77     .15       0
 2850.55     .12       0
Bank Sta=2272.45,2471.42
XS Rating Curve= 0
Exp/Cntr=.3,.1

Type RM Length L Ch R = 1 ,1164.962,46.53,46.59,46.54
BEGIN DESCRIPTION:
1164.962
END DESCRIPTION:
XS GIS Cut Line= 6
      3204678.51    13853169.175     3204576.463    13853010.587
     3204369.588    13852745.983     3204237.415    13852657.401
     3204153.411    13852633.876     3202604.637    13851702.687
#Sta/Elev= 30
       0   25.99  199.08   25.18  379.73   19.28  417.81   16.68  455.89   10.96
     536     7.3  562.15    4.39  568.18    6.03  568.22    6.03   586.2    -.92
   587.5      .4  591.83    -.94  593.53   -3.45  625.49   -4.59  639.36    3.36
  648.53    4.26  680.46    6.59  792.29    4.11  809.79    5.08   844.8   10.55
  914.81   12.74  949.81   11.96 1019.82   15.71 1107.33   13.81 1135.22   18.82
 1177.34   18.61 1282.36   23.02 1352.37   22.55 1439.88   25.47 2577.96   25.59
#Mann= 5 ,-1 , 0
       0     .12       0  379.73      .1       0  568.18    .045       0
  648.53      .1       0 1135.22     .12       0
Bank Sta=568.22,648.53
XS Rating Curve= 0
Exp/Cntr=.5,.3

Type RM Length L Ch R = 1 ,1118.375,51.19,51.21,51.51
BEGIN DESCRIPTION:
1118.375
END DESCRIPTION:
XS GIS Cut Line= 6
     3204709.207     13853136.74     3204626.893    13853007.224
     3204394.333    13852707.834      3204262.16    13852619.253
     3204193.925    13852600.014      3202643.25    13851657.226
#Sta/Elev= 30
       0   24.66   197.3   22.88  377.87   17.31  415.86   12.88   495.7   15.53
  556.94   14.33  586.88    3.75  603.14   -3.63  635.29   -4.72  648.27   -1.06
  649.38    3.36  664.36    7.53  667.14   13.82  687.98   14.74  699.11   11.46
  730.28   14.45  849.51   12.73     973   16.17 1131.78   15.15 1167.06   16.84
 1308.19    14.3 1323.05   17.75 1343.48   16.66  1396.4   22.62 1431.68   21.09
 1678.16   25.42 2016.76   23.77 2080.15   25.57 2272.41   24.31 2577.41   25.64
#Mann= 5 ,-1 , 0
       0     .12       0  377.87      .1       0  586.88    .045       0
  649.38      .1       0 1131.78     .12       0
#XS Ineff= 2 , 0
       0   560.9   16.29  666.68       0      16
Permanent Ineff=
       F       F
Bank Sta=586.88,649.38
XS Rating Curve= 0
Exp/Cntr=.5,.3

Type RM Length L Ch R = 3 ,1097.6  ,,,
BEGIN DESCRIPTION:
Market Street
END DESCRIPTION:
Bridge Culvert--1,0,-1,-1, 0
Deck Dist Width WeirC Skew NumUp NumDn MinLoCord MaxHiCord MaxSubmerge Is_Ogee
1,39.5,2.6,0, 26, 26, , , .95, 0, 0,0,,
   53.93  112.23  199.23  273.83  329.13  395.73  425.03  480.93  549.72  549.73
  576.33  621.33  661.73  661.74  666.74  729.33  784.03  849.23  960.43 1081.73
 1212.23 1326.33 1415.33 1422.97 1431.68 1437.04
      24      23      22      21      20      19      18      17   16.29   17.29
   17.41   17.41   17.37   16.37   16.34      16      16      17      18      19
      20      21      22   21.45   21.09   21.25
       0       0       0       0       0       0       0   12.81   12.81   12.81
   12.81   12.81   12.77   12.77   12.77       0       0       0       0       0
       0       0       0       0       0       0
   52.66  110.96  197.96  272.56  327.86  394.46  423.76  479.66  548.45  548.46
  575.06  620.06  660.46  660.47  665.47  728.06  782.76  847.96  959.16 1080.46
 1210.96 1325.06 1414.06 1422.97 1431.68 1437.04
    23.5      23      22      21      20      19      18      17   16.29   17.29
   17.41   17.41   17.37   16.37   16.34      16      16      17      18      19
      20      21      22   21.45   21.09   21.25
       0       0       0       0       0       0       0   12.81   12.81   12.81
   12.81   12.81   12.77   12.77   12.77       0       0       0       0       0
       0       0       0       0       0       0
Pier Skew, UpSta & Num, DnSta & Num=  ,603.33, 2 ,602.06, 2 , 0 , 0 , 0 ,,
     1.5     1.5
       0      15
     1.5     1.5
       0      15
Pier Skew, UpSta & Num, DnSta & Num=  ,635.33, 2 ,634.06, 2 , 0 , 0 , 0 ,,
     1.5     1.5
       0      15
     1.5     1.5
       0      15
BR Coef=-1 , 1 , 1 ,1.25, 0 ,,,.8,-1,2,0,
WSPro=,,,, 1 ,,,, 0 ,,,, 0 ,,,,-1 ,-1 ,-1 , 0 , 0 , 0 , 0 , 0
BC Design=,, 0 ,, 0 ,,,,,,

Type RM Length L Ch R = 1 ,1067.170,69.55,69.81,69.7
BEGIN DESCRIPTION:
1067.170: Ground Data shifted 18.6 ft to match upstream bridge encroachment.
END DESCRIPTION:
XS GIS Cut Line= 6
     3204764.812    13853037.299     3204571.339    13852777.438
     3204418.872    13852663.346      3204286.53    13852574.534
     3203043.927    13851671.556     3202755.659    13851511.979
#Sta/Elev= 30
    18.6   25.18  164.84   23.89  194.11   22.25  505.21   15.02   555.9    14.3
  576.85    6.23  581.92    5.92  588.06    2.84  602.02   -3.58  634.02   -4.72
     647   -1.06  648.12    3.35  648.18    3.37   656.9    4.84  664.48   14.68
  686.67   14.67  694.28    7.43  750.11    9.69  936.19    8.34   954.8     8.8
  973.41   11.71 1029.24   16.47 1066.45   17.52 1140.89   22.08 1402.87   25.67
 2017.63   26.29 2122.26   24.84 2267.22      26 2352.94    24.8 2557.93   25.26
#Mann= 6 ,-1 , 0
    18.6     .12       0  505.21     .06       0  588.06     .04       0
  648.12     .06       0 1066.45      .1       0 1140.89     .12       0
#XS Ineff= 2 , 0
    18.6  559.77   14.55     663    18.6   14.57
Permanent Ineff=
       F       F
Bank Sta=588.06,648.18
XS Rating Curve= 0
Exp/Cntr=.5,.3

Type RM Length L Ch R = 1 ,997.361 ,48.75,44.8,40.96
BEGIN DESCRIPTION:
997.361
END DESCRIPTION:
XS GIS Cut Line= 6
     3204779.033     13853004.66     3204563.652    13852731.321
     3204430.852     13852592.92     3204298.678    13852504.338
     3203706.514    13852063.877     3202782.705    13851477.827
#Sta/Elev= 30
       0   26.01  107.78   26.25  165.08   22.27  298.75   19.71  377.55   16.46
  481.49    9.81  523.07    6.32  585.84     2.8  589.23     .45  599.78   -3.66
  631.94   -4.72  652.83     1.8  706.19    1.74  734.66    3.03  828.13    2.69
  856.99     4.2 1007.79   16.19 1036.25   17.06 1109.22   22.64 1239.41   24.93
  1276.8   26.61 1351.58   26.95 1409.92   25.76 1749.62   26.26 1833.22   25.17
 1996.65   26.28  2188.1   24.82 2215.44   26.32 2437.74   24.99 2531.05   26.24
#Mann= 6 ,-1 , 0
       0     .12       0  377.55     .06       0  585.84     .04       0
  652.83     .06       0 1036.25      .1       0 1109.22     .12       0
Bank Sta=585.84,652.83
XS Rating Curve= 0
Exp/Cntr=.3,.1

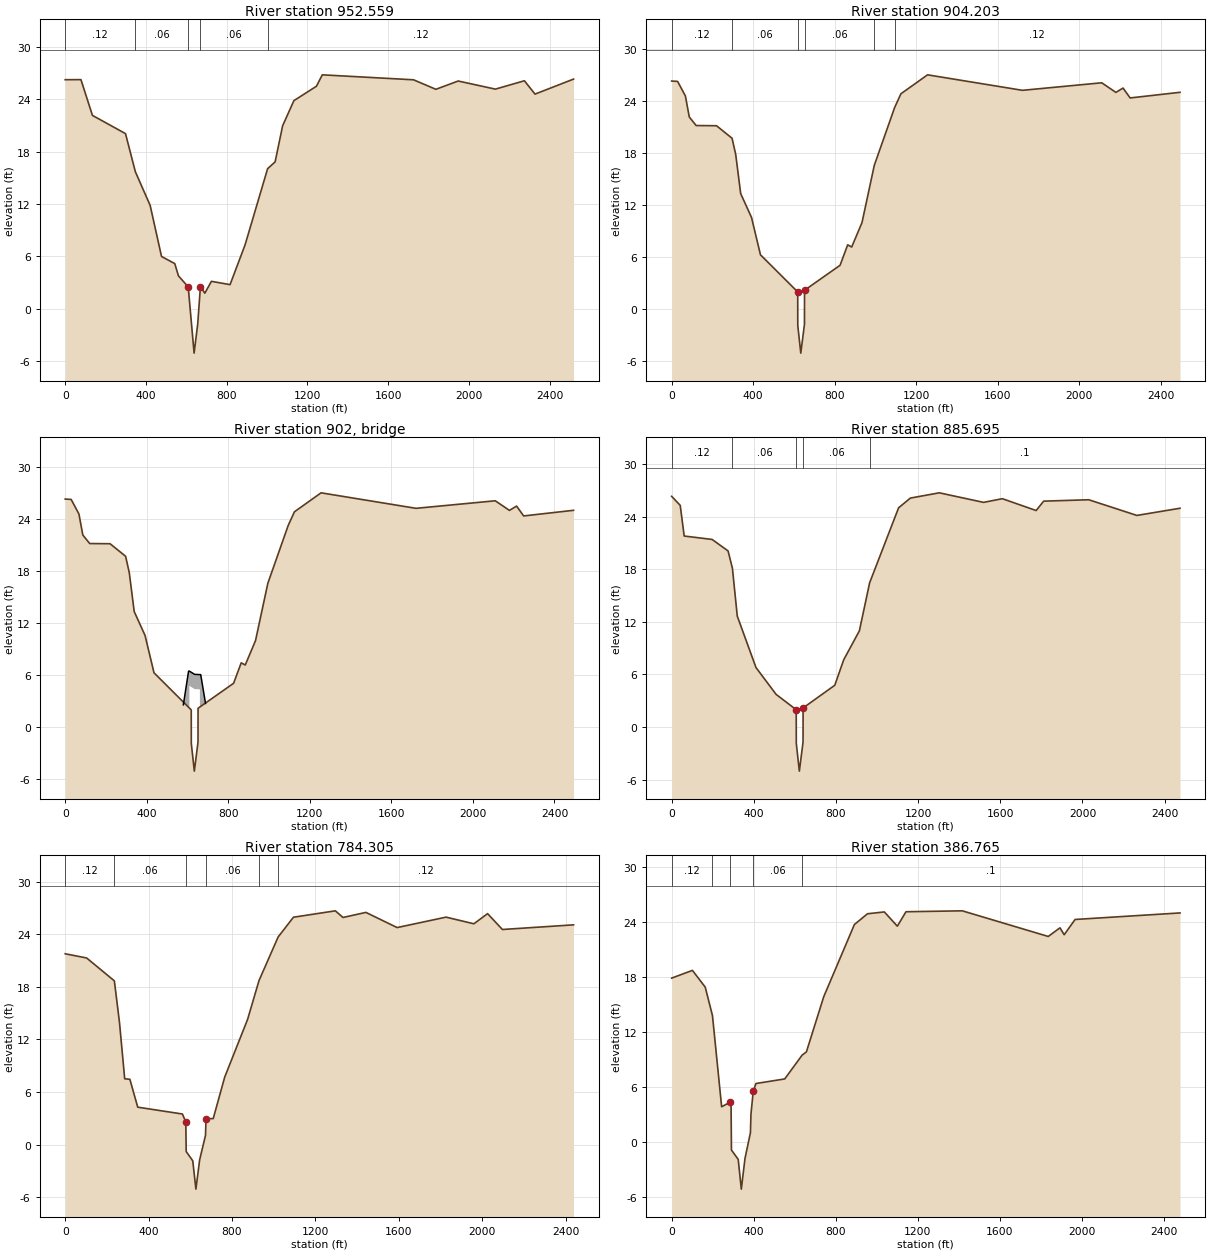
Type RM Length L Ch R = 1 ,952.559 ,48.36,48.36,48.36
BEGIN DESCRIPTION:
952.559
END DESCRIPTION:
XS GIS Cut Line= 6
     3204783.524    13852966.487     3204446.962    13852534.244
     3204280.044    13852461.817     3203702.155    13852037.722
     3203091.877     13851601.81     3202817.148    13851434.332
#Sta/Elev= 30
       0   26.24   77.93   26.25  134.96   22.15  298.72   20.06  347.55   15.69
   420.8   11.84  477.16    5.98  542.88    5.16  560.86    3.76  609.43    2.49
  638.54    -5.1  656.54   -1.75  669.87    2.53  691.67    1.77  724.37    3.13
  816.66    2.75  891.08    7.31 1002.71   16.04 1039.93   16.82 1077.14   20.96
 1132.96   23.84 1244.59   25.49 1273.71    26.8 1725.73   26.23 1836.33   25.14
 1946.94   26.09 2131.27   25.16 2274.88   26.12 2327.58   24.59 2518.31   26.31
#Mann= 5 ,-1 , 0
       0     .12       0  347.55     .06       0  609.43     .04       0
  669.87     .06       0 1002.71     .12       0
Bank Sta=609.43,669.87
XS Rating Curve= 0
Exp/Cntr=.4,.2

Type RM Length L Ch R = 1 ,904.203 ,18.5,18.51,18.51
BEGIN DESCRIPTION:
904.203
END DESCRIPTION:
XS GIS Cut Line= 6
     3204794.309    13852912.899     3204459.694     13852487.56
     3204292.776    13852415.133     3203758.823    13852020.286
     3203200.855    13851610.528     3202844.507    13851399.784
#Sta/Elev= 30
       0   26.33   29.14   26.29   67.31   24.61   86.39   22.18  120.18   21.19
  219.99   21.17  296.33   19.72  314.26   17.83  338.52   13.33  391.76   10.57
  435.56    6.26  618.26    1.97  618.55   -1.89  633.39    -5.1  651.39   -1.76
  651.68    2.16  826.09    5.05   863.4    7.41  883.14    7.16   933.6    9.98
  993.99    16.6  1093.8   23.28 1124.58   24.86 1255.17   27.05 1720.75   25.26
 2109.53   26.13 2179.23   25.02 2214.09   25.52 2248.94   24.38 2493.49   25.03
#Mann= 6 ,-1 , 0
       0     .12       0  296.33     .06       0  618.26     .04       0
  651.68     .06       0  993.99      .1       0  1093.8     .12       0
Bank Sta=618.26,651.68
XS Rating Curve= 0
Exp/Cntr=.4,.2

Type RM Length L Ch R = 3 ,902     ,,,
BEGIN DESCRIPTION:
Metal Pedestrian Bridge
END DESCRIPTION:
Bridge Culvert--1,0,-1,-1, 0
Deck Dist Width WeirC Skew NumUp NumDn MinLoCord MaxHiCord MaxSubmerge Is_Ogee
.203,4,2.6,0, 9, 9, , , .95, 0, 0,0,,
  579.58  605.15  609.15  609.16  634.69  660.64  660.65  664.65  688.34
    2.56    6.45    6.45    6.45    6.08    6.05    6.05    6.05    2.72
       0       0       0    4.75    4.38    4.35       0       0       0
  567.89  593.46  597.46  597.47     623  648.95  648.96  652.96  676.65
    2.56    6.45    6.45    6.45    6.08    6.05    6.05    6.05    2.72
       0       0       0    4.75    4.38    4.35       0       0       0
BR Coef=-1 , 0 , 0 ,, 0 ,,,.8,-1,,0,
WSPro=,,,, 1 ,,,, 0 ,,,, 0 ,,,,-1 ,-1 ,-1 , 0 , 0 , 0 , 0 , 0
BC Design=,, 0 ,, 0 ,,,,,,

Type RM Length L Ch R = 1 ,885.695 ,101.41,101.39,101.37
BEGIN DESCRIPTION:
885.695
END DESCRIPTION:
XS GIS Cut Line= 6
     3204802.827    13852877.124     3204469.764    13852471.954
     3204303.038    13852399.568     3204262.215    13852349.312
     3203789.337    13851976.694     3202879.057    13851356.156
#Sta/Elev= 30
       0   26.32   41.58   25.29      61   21.79  196.93    21.4   274.6   20.09
  295.78   18.11   319.4   12.65  410.52    6.78  508.37    3.72  606.34    1.97
  606.46    1.97  606.74   -1.86  621.56   -5.04  639.59   -1.74  639.88    2.16
  640.99    2.19  794.13    4.76  837.48    7.66  913.87   10.97  963.78   16.45
 1104.84   25.01 1162.13   26.12 1303.08   26.72 1518.52   25.63 1609.95   26.05
 1774.52    24.7 1811.09   25.77 2030.52   25.93 2265.12   24.14 2474.85   24.96
#Mann= 5 ,-1 , 0
       0     .12       0  295.78     .06       0  606.34     .04       0
  640.99     .06       0  963.78      .1       0
Bank Sta=606.34,640.99
XS Rating Curve= 0
Exp/Cntr=.4,.2

Type RM Length L Ch R = 1 ,784.305 ,377.57,397.54,417.5
BEGIN DESCRIPTION:
784.305
END DESCRIPTION:
XS GIS Cut Line= 6
     3204817.674     13852791.89     3204501.535    13852376.117
     3204388.065    13852326.881     3204334.616     13852303.69
     3203338.778    13851607.215     3202905.326    13851322.984
#Sta/Elev= 30
       0   21.76  102.87   21.28  235.72   18.67   260.5   13.89  285.29     7.5
  310.15    7.44  347.84    4.26  562.14    3.48  578.34    2.57  580.23     -.8
 611.735   -1.86 626.795   -5.09 644.755   -1.75  672.86    1.05  675.28    2.94
   709.9    2.96  764.81    7.68  874.64   14.27  929.56   18.71 1021.08   23.67
 1094.57   25.93 1295.65   26.66 1332.26    25.9 1442.08   26.48 1591.84   24.75
 1826.48   25.94    1960   25.18 2025.65   26.34 2096.78   24.53 2437.82   25.06
#Mann= 6 ,-1 , 0
       0     .12       0  235.72     .06       0  578.34     .04       0
  675.28     .06       0  929.56      .1       0 1021.08     .12       0
Bank Sta=578.34,675.28
XS Rating Curve= 0
Exp/Cntr=.3,.1

Type RM Length L Ch R = 1 ,386.765 ,395.24,386.77,378.3
BEGIN DESCRIPTION:
386.765
END DESCRIPTION:
XS GIS Cut Line= 6
     3204865.993    13852696.483     3204758.166     13852533.84
     3204738.404    13852439.414     3204708.068    13852294.473
     3203979.619     13851559.86     3203287.946    13850829.973
#Sta/Elev= 30
       0   17.87  101.33   18.71  163.75   16.89  199.06   13.79  243.73    3.87
   282.7    4.34  289.77    4.01  291.61    -.83 324.675   -1.86 339.735   -5.09
 357.695   -1.75  384.23    1.05  386.85    3.09  397.94    5.55  410.95     6.4
  551.61     6.9  636.11    9.48  657.24    9.84  741.73   15.84  891.42    23.7
  955.33   24.87 1037.47   25.07 1100.85   23.52  1143.1   25.09 1417.71   25.19
 1837.14    22.4 1894.25   23.34 1914.91   22.59 1967.98   24.25  2479.8   24.96
#Mann= 5 ,-1 , 0
       0     .12       0  199.06     .06       0   282.7     .04       0
  397.94     .06       0  636.11      .1       0
Bank Sta=282.7,397.94
XS Rating Curve= 0
Exp/Cntr=.3,.1

Chan Stop Cuts=-1